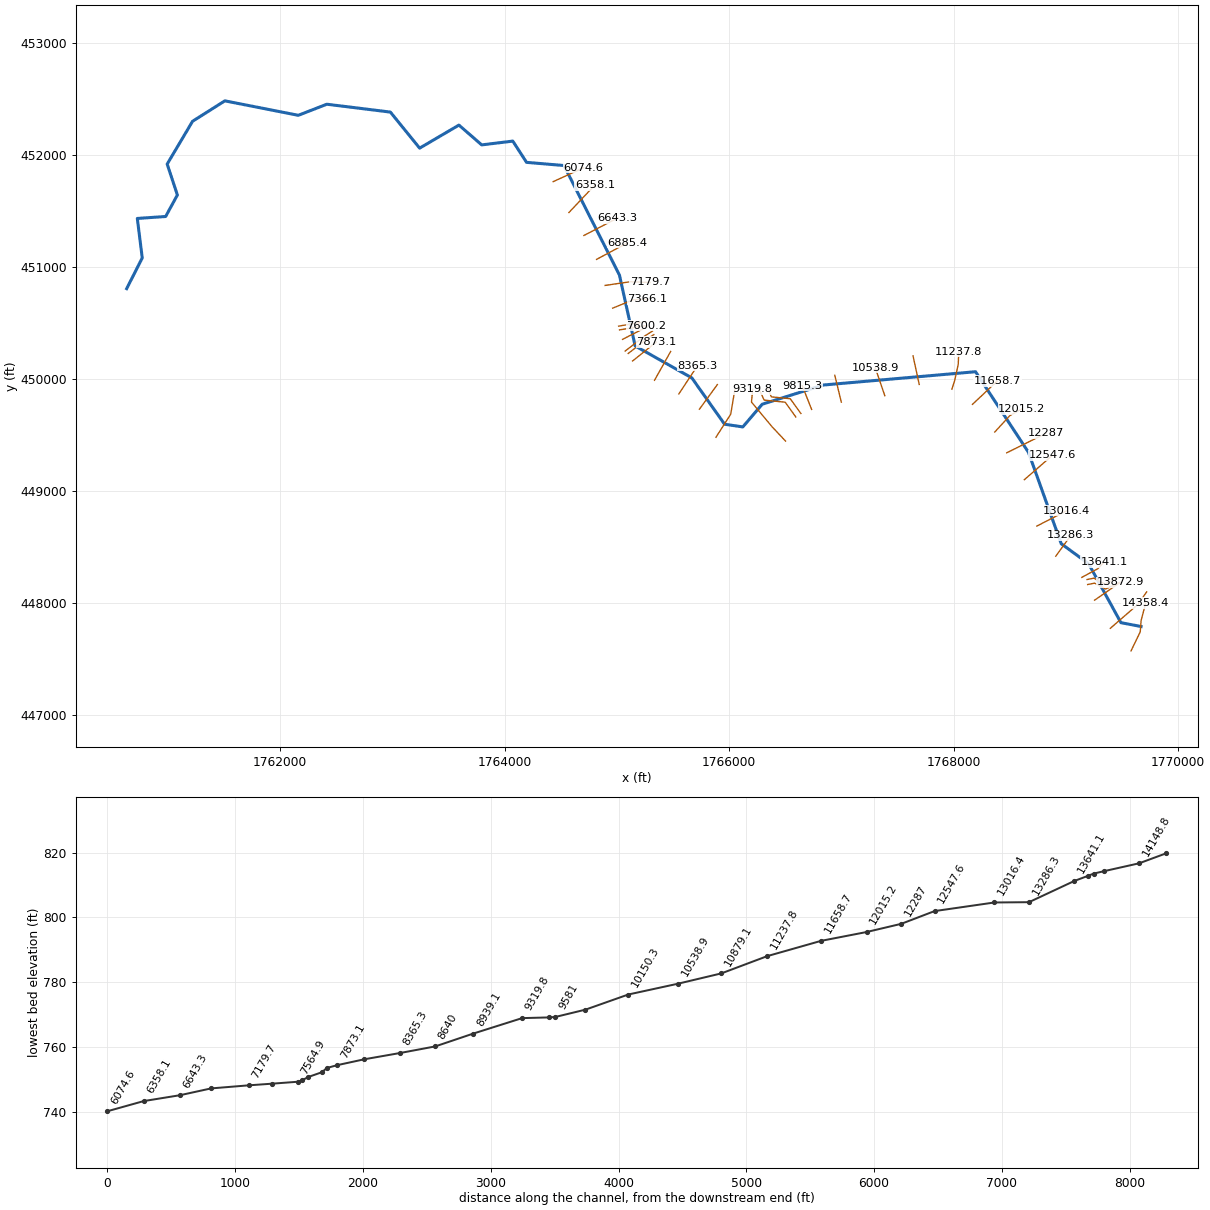
--- BRIERCK.prj (project) ---

Proj Title=BRIERCK
Current Plan=p01
Default Exp/Contr=0,0
English Units
Geom File=g01
Flow File=f01
Plan File=p01
BEGIN DESCRIPTION:
END DESCRIPTION:
DSS Export Rating Curves= 0
DSS Export Rating Curve Sorted= 0
DSS Export Volume Flow Curves= 0
DXF OffsetX= 0
DXF OffsetY= 0
DXF ScaleX= 0
DXF ScaleY= 0

--- BRIERCK.p01 (plan) ---

Plan Title=Floodplain
Program Version=4.00
Geom File=g01
Flow File=f01
K Sum by GR=0
Std Step Tol=0.01
Critical Tol=0.01
Num of Std Step Trials=20
Max Error Tol=0.3
Flow Tol Ratio=0.001
Split Flow NTrial=30
Split Flow Tol=0.02
Split Flow Ratio=0.02
Log Output Level=0
Friction Slope Method=1
Unsteady Friction Slope Method=2
Unsteady Bridges Friction Slope Method=1
Global Log Level=0
CheckData=False
Run HTab=0
Run UNet=0
Run PostProcess=0
UNET Theta=0
UNET Theta Warmup=0
UNET ZTol=0
UNET ZSATol=0
UNET MxIter=0
UNET MaxInSteps=0
UNET DtIC=0
UNET DtMin=0
UNET MaxCRTS=0
UNET WFStab=0
UNET SFStab=0
UNET WFX=0
UNET SFX=0
UNET DSS MLevel=0
UNET DZMax Abort=0
UNET Convert EG Bridges=0
UNET Use Existing IB Tables=0
UNET Froude Limit=0
UNET Froude Power=0
Write IC File=0
Echo Input=False
Echo Output=False
Write Detailed=0

--- BRIERCK.f01 (steady flow) ---

Flow Title=NFF Regression Equation
Program Version=4.10
Number of Profiles= 1
Profile Names=P100yr
River Rch & RM=BRIERCK,Main            ,14358.4
784.4565
River Rch & RM=BRIERCK,Main            ,13791.9
960.5107
River Rch & RM=BRIERCK,Main            ,10150.3
1031.135
River Rch & RM=BRIERCK,Main            ,6358.1
1378.769
River Rch & RM=BRIERCK,Main            ,3761.6
1617.549
River Rch & RM=BRIERCK,Main            ,752.6
1700.957
Boundary for River Rch & Prof#=BRIERCK,Main            , 1
Up Type= 0
Dn Type= 1
Dn Known WS=702.4
DSS Import GetInterval= 0
DSS Import GetPeak= 0
DSS Import FillOption= 0

--- BRIERCK.g01 (geometry) ---

Geom Title=USGS 10m DEM
Program Version=4.10

River Reach=BRIERCK         ,Main
Reach XY= 30
     1769669.407      447791.979     1769489.475      447826.535
     1769201.915      448351.661      1768957.48      448530.829
     1768665.836      449346.174     1768194.449       450065.09
     1766837.216      449946.325     1766294.253      449775.208
     1766121.712      449572.631     1765958.961      449596.591
     1765667.503      450009.716     1765162.445      450295.214
     1765022.433      450927.517     1764528.414      451904.461
     1764194.861       451932.76     1764072.619      452122.355
     1763795.721      452088.589     1763592.619      452265.133
     1763242.604      452059.496     1762982.187      452381.111
     1762415.985      452451.356     1762161.875      452352.465
      1761507.58      452481.456     1761219.937      452299.034
     1760993.848      451917.482     1761084.848        451641.4
     1760980.258      451449.785     1760727.956       451432.39
     1760771.871      451080.127     1760633.001      450806.208

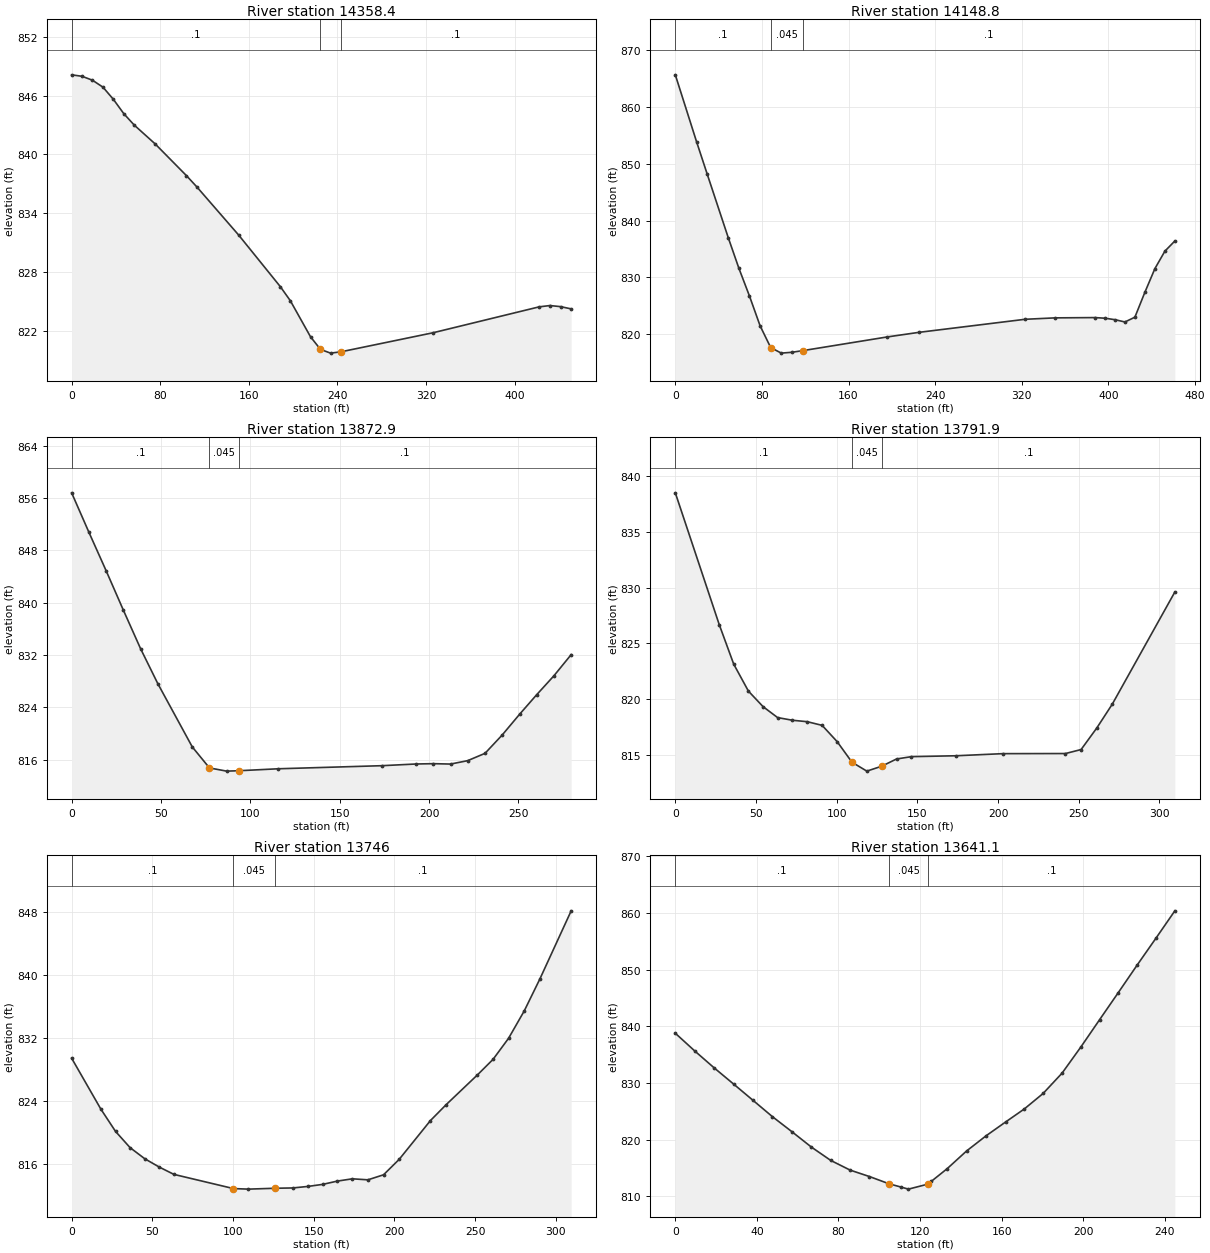
Type RM Length L Ch R = 1 ,14358.4 ,227.1,209.5,191.7
XS GIS Cut Line= 4
     1769579.608       447574.96     1769661.599      447744.659
     1769668.969      447844.085     1769710.233      448001.668
#Sta/Elev= 22
       0  848.12     9.4  847.97    18.8  847.57    28.3  846.86    37.7  845.62
    47.1  844.16    56.5     843    75.4  841.08   103.7  837.84   113.1  836.69
   150.8  831.79   188.5  826.52   197.5  825.09   215.7  821.42   224.7  820.13
   233.8  819.75     243  819.88   326.5  821.83   422.3  824.47   431.9   824.6
   441.5  824.49   451.1  824.26
#Mann= 3 , 0 , 0
       0      .1       0   224.7    .045       0     243      .1       0
Bank Sta=224.7,243
XS Rating Curve= 0 ,0
Exp/Cntr=0.3,0.1

Type RM Length L Ch R = 1 ,14148.8 ,278.3,275.9,273.5
XS GIS Cut Line= 3
     1769395.129      447776.321     1769639.053      447988.127
     1769718.914      448100.974
#Sta/Elev= 24
       0  865.64    19.6  853.89    29.4  848.21      49  836.94    58.7  831.63
    68.5  826.73    78.3   821.5    88.1  817.67    97.9   816.7   107.7  816.85
   117.5  817.13   195.8  819.55   225.2  820.36     323  822.65   350.7   822.9
   387.6  822.95   396.8  822.84     406  822.58   415.2  822.18   424.4  823.02
   433.6  827.39   442.9  831.57   452.1  834.63   461.3  836.42
#Mann= 3 , 0 , 0
       0      .1       0    88.1    .045       0   117.5      .1       0
Bank Sta=88.1,117.5
XS Rating Curve= 0 ,0
Exp/Cntr=0.3,0.1

Type RM Length L Ch R = 1 ,13872.9 ,107.2,81,54.9
XS GIS Cut Line= 2
     1769254.832      448026.967      1769484.17      448186.675
#Sta/Elev= 22
       0   856.8     9.6  850.81    19.3  844.89    28.9  838.89    38.6  832.96
    48.2  827.64    67.5  817.96    77.1  814.75    86.7  814.26    93.7  814.32
   115.6  814.62   173.5  815.09   192.7  815.35   202.4   815.4     212  815.34
   221.6  815.86   231.3  816.98   240.9  819.78   250.6  822.94   260.2  825.94
   269.8  828.82   279.5  832.07
#Mann= 3 , 0 , 0
       0      .1       0    77.1    .045       0    93.7      .1       0
Bank Sta=77.1,93.7
XS Rating Curve= 0 ,0
Exp/Cntr=0.3,0.1

Type RM Length L Ch R = 1 ,13791.9 ,67.7,46,40.5
XS GIS Cut Line= 4
     1769193.295      448166.878     1769255.519      448179.102
     1769352.432      448125.934      1769474.76      448184.574
#Sta/Elev= 22
       0  838.51    27.2  826.68    36.2  823.12    45.3   820.7    54.4   819.3
    63.4  818.32    72.6  818.08    81.8  817.95      91  817.62   100.3  816.16
   109.5  814.31   118.7  813.51   127.9  813.95   137.1   814.6   146.3  814.81
     174  814.89     203  815.08   241.8  815.09   251.5  815.45   261.2  817.38
   270.8  819.52   309.6   829.6
#Mann= 3 , 0 , 0
       0      .1       0   109.5    .045       0   127.9      .1       0
Bank Sta=109.5,127.9
XS Rating Curve= 0 ,0
Exp/Cntr=0.3,0.1

Type RM Length L Ch R = 1 ,13746   ,59.2,104.9,133.5
XS GIS Cut Line= 4
     1769186.932      448211.127     1769249.155       448223.35
     1769346.068      448170.183     1769468.396      448228.822
#Sta/Elev= 26
       0  829.41    18.1  822.95    27.2  820.12    36.2  818.06    45.3  816.65
    54.4  815.58    63.4  814.66   100.3  812.86   109.5  812.79     126   812.9
   137.1  812.94   146.3  813.13   155.5  813.39   164.7  813.81     174   814.1
   183.6  813.97   193.3  814.61     203  816.57   222.4   821.5   232.1  823.51
   251.5  827.29   261.2  829.27   270.8  831.94   280.5  835.41   290.2  839.47
   309.6  848.12
#Mann= 3 , 0 , 0
       0      .1       0   100.3    .045       0     126      .1       0
Bank Sta=100.3,126
XS Rating Curve= 0 ,0
Exp/Cntr=0.3,0.1

Type RM Length L Ch R = 1 ,13641.1 ,344.6,354.8,364.9
XS GIS Cut Line= 3
     1769140.682      448230.432     1769283.043      448307.515
     1769340.682      448367.238
#Sta/Elev= 29
       0  838.77     9.5  835.65      19  832.67    28.6  829.79    38.1  826.92
    47.6  824.04    57.1   821.4    66.7  818.67    76.2  816.31    85.7   814.6
    95.2  813.46   104.8  812.18   110.5  811.62   114.3  811.24   123.8  812.12
   125.5  812.61   133.3  814.86   142.8  817.98   152.4  820.67   161.9  823.09
   171.1   825.4   180.3  828.13   189.6  831.72   198.8  836.33     208  841.16
   217.2  845.96   226.4   850.8   235.7  855.59   244.9  860.39
#Mann= 3 , 0 , 0
       0      .1       0   104.8    .045       0   123.8      .1       0
Bank Sta=104.8,123.8
XS Rating Curve= 0 ,0
Exp/Cntr=0.3,0.1

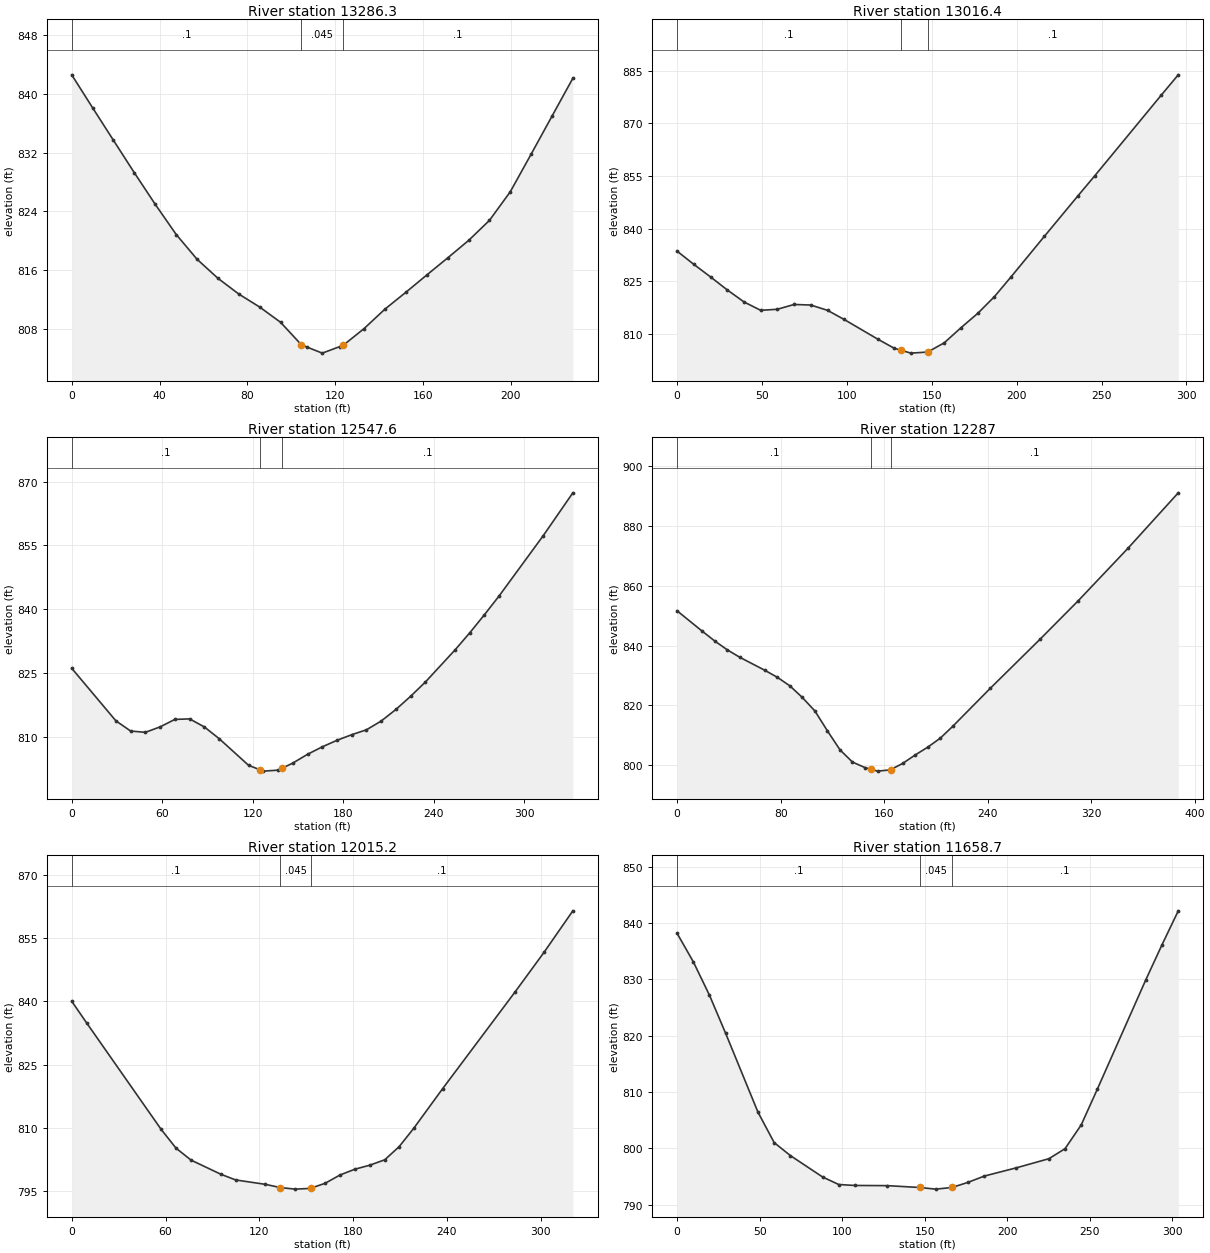
Type RM Length L Ch R = 1 ,13286.3 ,280.3,270,258.9
XS GIS Cut Line= 2
     1768909.146      448419.436     1769042.964      448604.336
#Sta/Elev= 27
       0  842.58     9.5   838.1      19  833.67    28.5  829.26      38  824.97
    47.6  820.84    57.1  817.47    66.6  814.88    76.1  812.74    85.6  810.97
    95.1   808.9   104.6  805.83     107  805.54   114.1   804.7     122  805.58
   123.6  805.76   133.1  808.03   142.6  810.68   152.2  812.99   161.7  815.34
   171.2  817.66   180.7  820.03   190.2  822.76   199.7  826.66   209.2  831.78
   218.7  836.95   228.2  842.11
#Mann= 3 , 0 , 0
       0      .1       0   104.6    .045       0   123.6      .1       0
Bank Sta=104.6,123.6
XS Rating Curve= 0 ,0
Exp/Cntr=0.3,0.1

Type RM Length L Ch R = 1 ,13016.4 ,462.8,468.7,474
XS GIS Cut Line= 2
      1768740.87      448688.289     1769003.154      448823.644
#Sta/Elev= 26
       0  833.61     9.8  829.87    19.7  826.28    29.5   822.6    39.4  819.17
    49.2  816.79      59  817.08    68.9  818.45    78.7  818.29    88.6  816.78
    98.4  814.18   118.1  808.61   127.9  805.99   131.6  805.47   137.7  804.61
   147.6  804.92   157.4  807.56   167.2  811.83   177.1  815.93   186.9  820.67
   196.8  826.36   216.4  837.87   236.1  849.35     246  855.04   285.3  878.06
   295.2  883.77
#Mann= 3 , 0 , 0
       0      .1       0   131.6    .045       0   147.6      .1       0
Bank Sta=131.6,147.6
XS Rating Curve= 0 ,0
Exp/Cntr=0.3,0.1

Type RM Length L Ch R = 1 ,12547.6 ,266,260.6,254.5
XS GIS Cut Line= 2
     1768629.148      449101.939     1768880.259      449319.717
#Sta/Elev= 30
       0  826.12    29.3  813.77    39.1  811.37    48.9  811.07    58.7  812.36
    68.4   814.1    78.2  814.23      88  812.33    97.8  809.58   117.3  803.32
   124.7  802.29   127.1  801.95   136.9  802.18   139.7  802.66   146.6  803.83
   156.4   805.9   166.2  807.66     176   809.2   185.8  810.52   195.5  811.66
   205.3  813.73   215.1  816.46   224.8  819.54   234.6  822.89   254.2  830.41
     264  834.44   273.7  838.68   283.5  843.12   312.8   857.3   332.4  867.35
#Mann= 3 , 0 , 0
       0      .1       0   124.7    .045       0   139.7      .1       0
Bank Sta=124.7,139.7
XS Rating Curve= 0 ,0
Exp/Cntr=0.3,0.1

Type RM Length L Ch R = 1 ,12287   ,263.1,271.8,279.6
XS GIS Cut Line= 2
     1768472.724      449341.939     1768819.252      449514.161
#Sta/Elev= 28
       0  851.67    19.4  844.85      29  841.59    38.7  838.63    48.4  836.12
    67.7  831.78    77.4  829.42    87.1  826.55    96.7  822.67   106.4  818.15
   116.1  811.48   125.8  805.13   135.4  801.05   145.1   799.2   150.1  798.59
   154.8  798.02   164.5  798.43   165.1  798.56   174.1  800.58   183.8  803.41
   193.5  806.03   203.2  809.04   212.8     813   241.8  825.73   280.6  842.31
   309.6  854.98   348.3  872.68     387  891.17
#Mann= 3 , 0 , 0
       0      .1       0   150.1    .045       0   165.1      .1       0
Bank Sta=150.1,165.1
XS Rating Curve= 0 ,0
Exp/Cntr=0.3,0.1

Type RM Length L Ch R = 1 ,12015.2 ,357.5,356.5,353.9
XS GIS Cut Line= 3
     1768365.795      449527.321     1768501.231      449674.717
     1768606.786      449732.494
#Sta/Elev= 23
       0     840     9.5  834.89    57.2  809.64    66.7   805.2    76.3  802.37
    95.3  799.03   104.8  797.67   123.9  796.62   133.4  795.86     143  795.49
   152.5  795.66   153.2  795.75     162  796.86   171.6  798.84   181.1  800.21
   190.6  801.16   200.2  802.44   209.4  805.55   218.7  809.88   237.2  819.28
   283.5  842.18     302  851.55   320.5  861.42
#Mann= 3 , 0 , 0
       0      .1       0   133.4    .045       0   153.2      .1       0
Bank Sta=133.4,153.2
XS Rating Curve= 0 ,0
Exp/Cntr=0.3,0.1

Type RM Length L Ch R = 1 ,11658.7 ,406.7,420.9,434.4
XS GIS Cut Line= 2
     1768167.301      449774.066     1768388.269      449982.226
#Sta/Elev= 24
       0  838.17     9.8  833.13    19.6  827.19    29.4  820.42      49  806.41
    58.8  801.02    68.6  798.72    88.1  794.92    97.9  793.58   107.7  793.41
   127.3  793.38   146.9  793.05   156.7  792.76   166.5  793.05   176.3  793.97
   186.1  795.08   205.6  796.55   225.2  798.16     235  799.94   244.8  804.16
   254.6  810.53     284  829.97   293.8  836.18   303.6  842.18
#Mann= 3 , 0 , 0
       0      .1       0   146.9    .045       0   166.5      .1       0
Bank Sta=146.9,166.5
XS Rating Curve= 0 ,0
Exp/Cntr=0.3,0.1

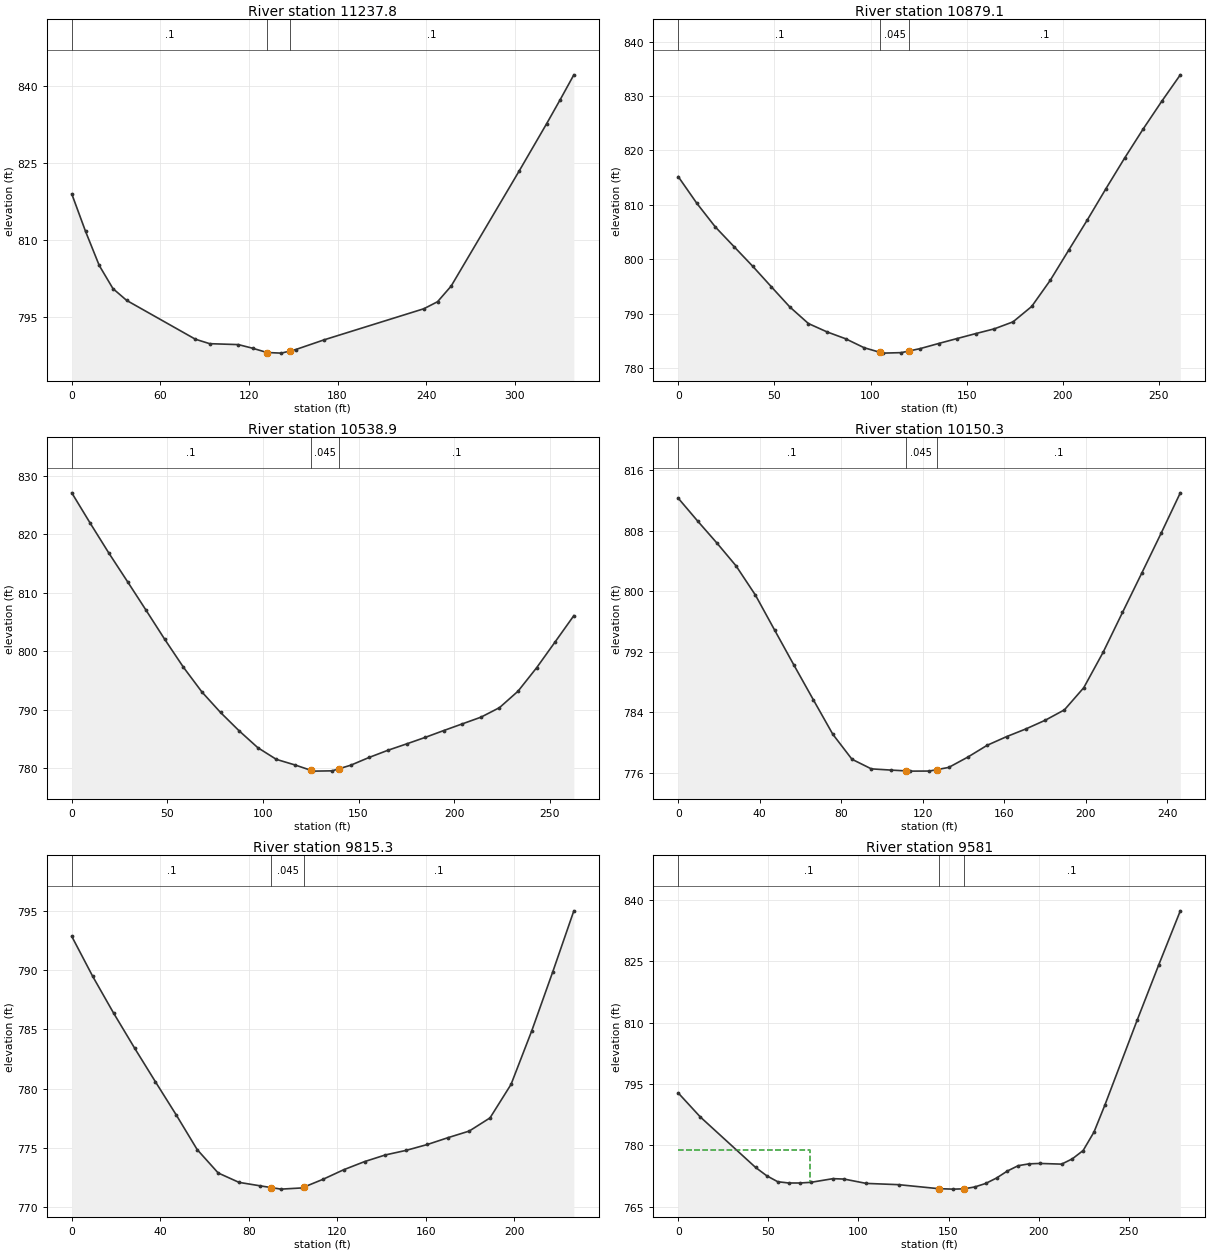
Type RM Length L Ch R = 1 ,11237.8 ,348.8,358.6,367.9
XS GIS Cut Line= 4
     1767983.835        449909.3     1768009.385      449989.042
     1768040.259      450131.175     1768044.946      450241.939
#Sta/Elev= 21
       0  819.05     9.3  811.78    18.6  805.12    27.9  800.61    37.2  798.31
    83.7  790.76    93.4  789.89   112.8  789.71   122.5     789   132.2  788.17
   141.9  788.05     148  788.48   151.6  788.74     171  790.65   238.4  796.69
   247.7  798.06   256.9   801.1   303.1  823.58   321.6  832.74   330.8  837.43
     340  842.24
#Mann= 3 , 0 , 0
       0      .1       0   132.2    .045       0     148      .1       0
Bank Sta=132.2,148
XS Rating Curve= 0 ,0
Exp/Cntr=0.3,0.1

Type RM Length L Ch R = 1 ,10879.1 ,337.5,340.2,342.8
XS GIS Cut Line= 2
     1767692.863      449951.661     1767637.655      450206.869
#Sta/Elev= 30
       0  815.19     9.7  810.27    19.3  805.93      29  802.32    38.7  798.72
    48.4  794.94      58  791.23    67.7  788.17    77.4  786.63      87  785.38
    96.7  783.72   105.1  782.86   106.4  782.73     116  782.82   120.1  783.13
   125.7  783.55   135.4   784.5   145.1  785.42   154.7  786.32   164.4   787.2
   174.1  788.48   183.8  791.31   193.4  796.09   203.1  801.69   212.8  807.26
   222.4  812.96   232.1  818.58   241.8  823.96   251.4  829.02   261.1  833.91
#Mann= 3 , 0 , 0
       0      .1       0   105.1    .045       0   120.1      .1       0
Bank Sta=105.1,120.1
XS Rating Curve= 0 ,0
Exp/Cntr=0.3,0.1

Type RM Length L Ch R = 1 ,10538.9 ,390.4,388.5,386.6
XS GIS Cut Line= 2
     1767386.321      449850.833     1767301.488      450099.364
#Sta/Elev= 30
       0  827.11     9.7  821.89    19.4  816.81    29.2  811.91    38.9  807.02
    48.6  802.08    58.4   797.3    68.1  793.06    77.8  789.57    87.5  786.44
    97.3  783.55     107  781.55   116.7   780.6   124.9   779.7   126.4  779.54
   136.2  779.59   139.9  779.96   145.9  780.55   155.6  781.89   165.4  783.11
   175.1  784.19   184.8   785.3   194.5  786.47   204.2  787.61     214  788.76
   223.7  790.39   233.4   793.2   243.2  797.24   252.9  801.67   262.6  806.12
#Mann= 3 , 0 , 0
       0      .1       0   124.9    .045       0   139.9      .1       0
Bank Sta=124.9,139.9
XS Rating Curve= 0 ,0
Exp/Cntr=0.3,0.1

Type RM Length L Ch R = 1 ,10150.3 ,331.2,335,337.7
XS GIS Cut Line= 2
     1766998.939      449793.478      1766940.78      450033.062
#Sta/Elev= 29
       0  812.29     9.5  809.28      19  806.36    28.4  803.34    37.9  799.48
    47.4  794.82    56.9  790.18    66.4  785.61    75.9  781.08    85.3  777.78
    94.8  776.51   104.3  776.35   111.8  776.24   113.8  776.21   123.3  776.22
   126.8   776.4   132.8   776.7   142.2  778.07   151.7  779.63   161.2  780.77
   170.7  781.79   180.2  782.94   189.6  784.31   199.1  787.24   208.6  791.92
   218.1  797.18   227.6   802.4   237.1  807.67   246.5     813
#Mann= 3 , 0 , 0
       0      .1       0   111.8    .045       0   126.8      .1       0
Bank Sta=111.8,126.8
XS Rating Curve= 0 ,0
Exp/Cntr=0.3,0.1

Type RM Length L Ch R = 1 ,9815.3  ,168.3,234.4,265.7
XS GIS Cut Line= 2
     1766734.287      449728.868     1766650.953      449939.979
#Sta/Elev= 27
       0  792.83     9.5  789.45    18.9  786.37    28.4  783.42    37.8  780.59
    47.3  777.77    56.7  774.87    66.2   772.9    75.6  772.11    85.1  771.82
    90.2  771.67    94.6  771.54     104  771.64   105.2  771.73   113.5  772.36
   122.9  773.17   132.4  773.86   141.8  774.42   151.3  774.81   160.8   775.3
   170.2  775.88   179.7  776.43   189.1  777.54   198.6  780.36     208  784.89
   217.5  789.86     227  794.98
#Mann= 3 , 0 , 0
       0      .1       0    90.2    .045       0   105.2      .1       0
Bank Sta=90.2,105.2
XS Rating Curve= 0 ,0
Exp/Cntr=0.3,0.1

Type RM Length L Ch R = 1 ,9581    ,86.6,47.5,119.3
XS GIS Cut Line= 4
     1766638.532      449692.381     1766543.889      449824.191
     1766375.942      449840.731     1766335.563      449934.866
#Sta/Elev= 30
       0  792.81  12.277  786.93  42.938   774.6  49.109  772.57  55.215  771.11
  61.322   770.8  67.493   770.8  73.599  770.96  85.876  771.86  92.047  771.76
 104.324   770.7 122.387  770.39 144.563  769.41 152.534   769.3 158.511  769.37
 164.554  769.83 170.596  770.68 176.638  772.01  182.68  773.73 188.658  775.03
   194.7  775.48 200.743  775.58 212.763  775.41 218.741  776.71 224.719  778.74
 230.761  783.27 236.739   789.8 254.672  810.57 266.628  824.07 278.648  837.33
#Mann= 3 , 0 , 0
       0      .1       0 144.563    .045       0 158.511      .1       0
#XS Ineff= 2 , 0
          73.284  778.78
Permanent Ineff=
       F       F
Bank Sta=144.563,158.511
XS Rating Curve= 0 ,0
Skew Angle= 50
Exp/Cntr=0.3,0.1

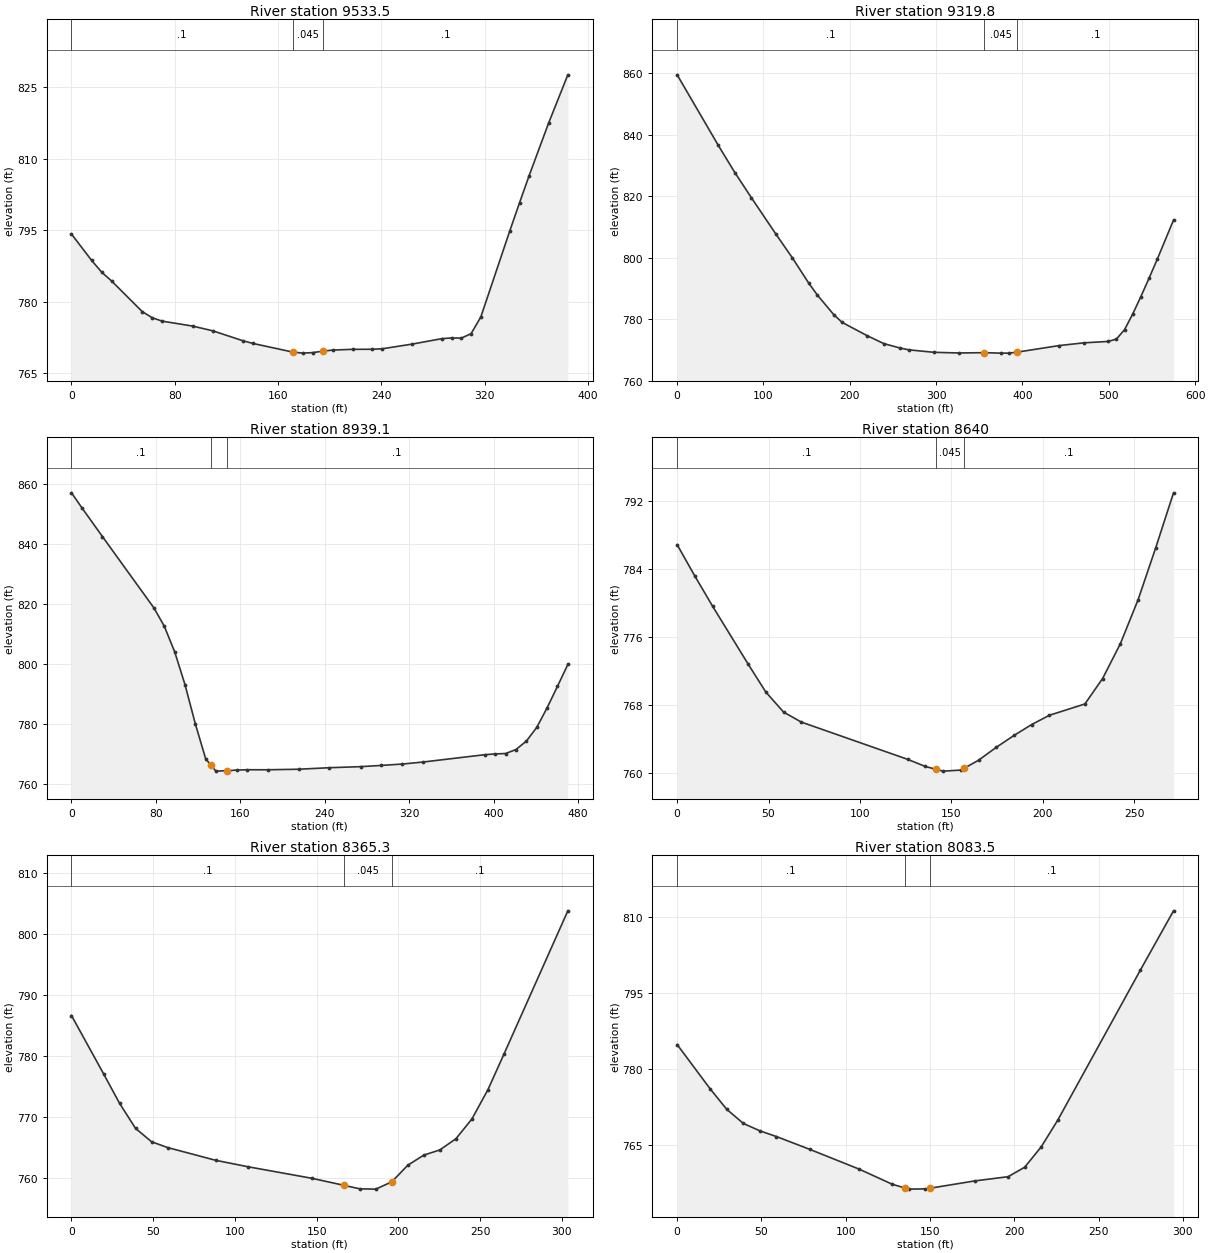
Type RM Length L Ch R = 1 ,9533.5  ,233.8,213.7,117
XS GIS Cut Line= 4
     1766593.393      449661.478      1766498.75      449793.288
     1766311.457      449811.733     1766261.813      449919.866
#Sta/Elev= 30
       0  794.18  15.646  788.63  23.428  786.16  31.292  784.26  54.719   777.9
  62.583  776.58  70.365  775.87  93.793  774.84 109.439  773.84 132.948  771.74
 140.648  771.18 171.449  769.37 179.149  769.15 186.849  769.26 194.631  769.56
 202.331  769.79 217.731  769.95 233.131  769.96 240.831  770.07 263.931  771.05
 287.113   772.2 294.567  772.34 302.103  772.32 309.558  773.24 317.094  776.75
 339.539  794.85 347.075  800.75 354.529  806.47 369.601  817.51  384.51  827.66
#Mann= 3 , 0 , 0
       0      .1       0 171.449    .045       0 194.631      .1       0
Bank Sta=171.449,194.631
XS Rating Curve= 0 ,0
Skew Angle= 35
Exp/Cntr=0.3,0.1

Type RM Length L Ch R = 1 ,9319.8  ,408.2,380.7,351.9
XS GIS Cut Line= 4
     1766502.041      449446.723     1766384.161      449571.664
     1766198.592      449794.346     1766209.009      449907.193
#Sta/Elev= 30
       0  859.53    47.7  836.54    66.8  827.73    85.9  819.56   114.5  807.63
   133.6  799.89   152.7   791.6   162.2  787.92   181.4  781.46   191.1  778.94
   220.1  774.61   239.4  772.03   258.7  770.56   268.4     770   297.4   769.2
   326.4  768.98   355.4  769.08   374.7  768.93   384.3  768.93     394  769.26
   442.3  771.38   471.1  772.28   499.4  772.74   508.9  773.52   518.3  776.58
   527.8   781.7   537.2  787.35   546.6  793.28   556.1  799.45     575  812.25
#Mann= 3 , 0 , 0
       0      .1       0   355.4    .045       0     394      .1       0
Bank Sta=355.4,394
XS Rating Curve= 0 ,0
Exp/Cntr=0.3,0.1

Type RM Length L Ch R = 1 ,8939.1  ,299.5,299.1,297.8
XS GIS Cut Line= 3
     1765882.009      449480.339     1766013.723       449686.19
     1766051.023      449908.946
#Sta/Elev= 30
       0   856.9     9.8  851.94    29.3  842.34    78.2   818.5      88   812.4
    97.8  803.89   107.5  793.04   117.3  779.96   127.1   768.3   131.9  766.26
   136.8  764.18   146.9  764.32   156.4  764.53   166.2  764.64   185.7  764.63
   215.1  764.81   244.4  765.32   273.8  765.67   293.5  766.08   313.1  766.53
   332.8   767.2   391.7  769.66   401.5  769.91   411.3  770.05   421.1  771.38
     431  774.22   440.8  778.77   450.6   785.3   460.4  792.45   470.2  799.72
#Mann= 3 , 0 , 0
       0      .1       0   131.9    .045       0   146.9      .1       0
Bank Sta=131.9,146.9
XS Rating Curve= 0 ,0
Exp/Cntr=0.3,0.1

Type RM Length L Ch R = 1 ,8640    ,274.2,274.7,274.3
XS GIS Cut Line= 2
      1765735.05      449730.978     1765894.773      449950.596
#Sta/Elev= 24
       0  786.87     9.7  783.17    19.4  779.62    38.8  772.82    48.5  769.52
    58.2  767.16    67.9  765.98   126.1  761.59   135.8  760.75   141.9   760.4
   145.5   760.2   155.2  760.32   156.9  760.52   164.9  761.48   174.6     763
   184.3   764.4     194  765.69   203.7  766.78   223.1  768.11   232.8  771.11
   242.5   775.2   252.2  780.38   261.9  786.53   271.6  792.98
#Mann= 3 , 0 , 0
       0      .1       0   141.9    .045       0   156.9      .1       0
Bank Sta=141.9,156.9
XS Rating Curve= 0 ,0
Exp/Cntr=0.3,0.1

Type RM Length L Ch R = 1 ,8365.3  ,279.7,281.8,282.8
XS GIS Cut Line= 2
     1765551.543      449867.089     1765718.905      450120.562
#Sta/Elev= 21
       0  786.64    19.6   777.1    29.4  772.25    39.2  768.13      49  765.94
    58.8  764.99    88.2   762.9   107.8  761.85     147  759.95   166.6   758.8
   176.4  758.22   186.2  758.17     196  759.37   205.8   762.1   215.6  763.75
   225.4   764.6   235.2  766.43     245  769.67   254.8  774.48   264.6   780.3
   303.7  803.81
#Mann= 3 , 0 , 0
       0      .1       0   166.6    .045       0     196      .1       0
Bank Sta=166.6,196
XS Rating Curve= 0 ,0
Exp/Cntr=0.3,0.1

Type RM Length L Ch R = 1 ,8083.5  ,219.6,210.4,200.8
XS GIS Cut Line= 2
     1765334.877      449988.617     1765478.627      450245.562
#Sta/Elev= 20
       0  784.83    19.6  776.05    29.4  772.02    39.3  769.21    49.1  767.75
    58.9  766.62    78.5  764.11     108  760.17   127.6  757.18     135  756.46
   137.4  756.22   147.2  756.27     150   756.4   176.6  757.85   196.3  758.68
   206.1  760.55   215.9  764.57   225.7  769.85   274.8   799.6   294.4  811.29
#Mann= 3 , 0 , 0
       0      .1       0     135    .045       0     150      .1       0
Bank Sta=135,150
XS Rating Curve= 0 ,0
Exp/Cntr=0.3,0.1

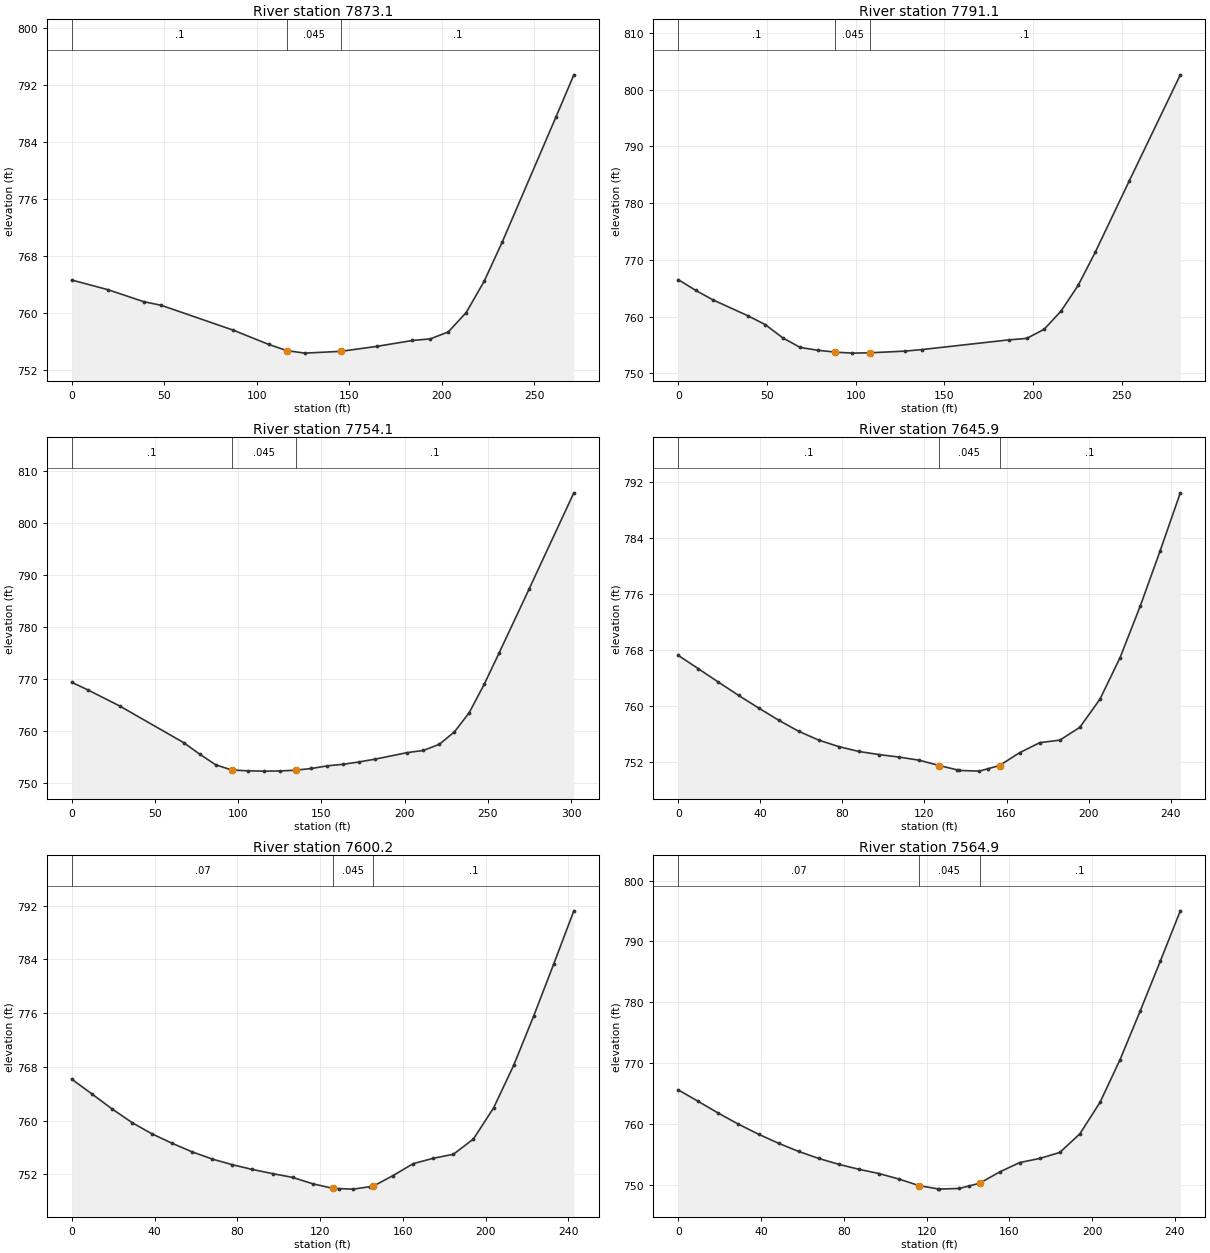
Type RM Length L Ch R = 1 ,7873.1  ,81.4,82,82.1
XS GIS Cut Line= 2
     1765139.375      450160.398     1765351.042      450330.398
#Sta/Elev= 18
       0  764.66    19.4  763.32    38.8  761.64    48.5  761.11    87.3  757.64
   106.6  755.63   116.4  754.77     126  754.42   145.4  754.67   164.8  755.36
   184.2  756.19   193.9  756.42   203.6  757.39   213.3  760.11     223  764.49
   232.7  769.94   261.8  787.49   271.5  793.41
#Mann= 3 , 0 , 0
       0      .1       0   116.4    .045       0   145.4      .1       0
Bank Sta=116.4,145.4
XS Rating Curve= 0 ,0
Exp/Cntr=0.3,0.1

Type RM Length L Ch R = 1 ,7791.1  ,35.7,37,44
XS GIS Cut Line= 3
     1765100.787      450227.979     1765263.749      450354.492
     1765328.472      450395.858
#Sta/Elev= 21
       0  766.51     9.8  764.62    19.6  762.93    39.3  760.13    49.1  758.57
    58.9  756.24    68.8  754.54    78.6  754.05    88.4  753.72    98.2  753.54
   108.1   753.6   127.7  753.89   137.5  754.17   186.7  755.89   196.5  756.14
   206.3  757.74   215.9  760.98   225.5   765.5   235.1  771.32   254.3  783.92
   283.1  802.64
#Mann= 3 , 0 , 0
       0      .1       0    88.4    .045       0   108.1      .1       0
Bank Sta=88.4,108.1
XS Rating Curve= 0 ,0
Exp/Cntr=0.3,0.1

Type RM Length L Ch R = 1 ,7754.1  ,113.4,108.2,96.7
XS GIS Cut Line= 3
     1765073.356      450249.507      1765248.13      450384.389
     1765316.806      450427.108
#Sta/Elev= 25
       0  769.35     9.6   767.9    28.8  764.79    67.2  757.74    76.8  755.53
    86.4  753.48      96  752.47   105.6  752.31   115.2  752.25   124.8  752.28
   134.4  752.43     144  752.76   153.6  753.27   163.2  753.58   172.8  754.03
   182.4  754.57   201.6  755.82   211.2  756.23   220.8  757.42   229.8  759.79
   238.7  763.48   247.7  768.94   256.7     775   274.7   787.3   301.6  805.83
#Mann= 3 , 0 , 0
       0      .1       0      96    .045       0   134.4      .1       0
Bank Sta=96,134.4
XS Rating Curve= 0 ,0
Exp/Cntr=0.3,0.1

Type RM Length L Ch R = 1 ,7645.9  ,52.8,45.8,38.7
XS GIS Cut Line= 2
     1765049.792      450353.731     1765267.708      450464.981
#Sta/Elev= 28
       0  767.27     9.8  765.36    19.6  763.45    29.4  761.56    39.2  759.76
    48.9  758.03    58.7  756.44    68.5  755.18    78.3  754.25    88.1  753.56
    97.9  753.12   107.7  752.76   117.4  752.32   127.2  751.56   135.8  750.95
     137  750.86   146.8  750.76   150.8  751.09   156.6  751.56   166.4  753.39
   176.2  754.82     186  755.18   195.7     757   205.5     761   215.3  766.92
   225.1  774.24   234.9   782.2   244.7  790.44
#Mann= 3 , 0 , 0
       0      .1       0   127.2    .045       0   156.6      .1       0
Bank Sta=127.2,156.6
XS Rating Curve= 0 ,0
Exp/Cntr=0.3,0.1

Type RM Length L Ch R = 1 ,7600.2  ,35.3,35.3,35.3
XS GIS Cut Line= 2
     1765023.313      450438.287     1765262.746      450477.362
#Sta/Elev= 28
       0  766.17     9.7  763.97    19.4  761.75    29.1   759.7    38.8  758.01
    48.5  756.61    58.2  755.33    67.9  754.26    77.6  753.42    87.3  752.71
      97  752.09   106.7  751.53   116.4  750.58   126.2  749.89   129.2  749.86
   135.9  749.78   144.2  750.15   145.6  750.21   155.3  751.81     165  753.58
   174.7  754.38   184.4  754.97   194.1  757.26   203.8  761.87   213.5  768.21
   223.2  775.58   232.9  783.35   242.6  791.25
#Mann= 3 , 0 , 0
       0     .07       0   126.2    .045       0   145.6      .1       0
Bank Sta=126.2,145.6
XS Rating Curve= 0 ,0
Exp/Cntr=0.3,0.1

Type RM Length L Ch R = 1 ,7564.9  ,193.5,198.8,203.8
XS GIS Cut Line= 2
      1765014.98      450472.037     1765254.413      450511.112
#Sta/Elev= 28
       0  765.61     9.7  763.71    19.4  761.78    29.1  759.97    38.8  758.32
    48.5  756.83    58.2  755.49    67.9  754.34    77.6  753.37    87.3  752.56
      97  751.86   106.7  750.95   116.4  749.87   125.5  749.34   126.2   749.3
   135.9  749.42   140.5  749.82   145.6  750.26   155.3  752.12     165  753.67
   174.7  754.34   184.4  755.33   194.1   758.4   203.8  763.56   213.5  770.59
   223.2  778.56   232.9  786.73   242.6  795.02
#Mann= 3 , 0 , 0
       0     .07       0   116.4    .045       0   145.6      .1       0
Bank Sta=116.4,145.6
XS Rating Curve= 0 ,0
Exp/Cntr=0.3,0.1

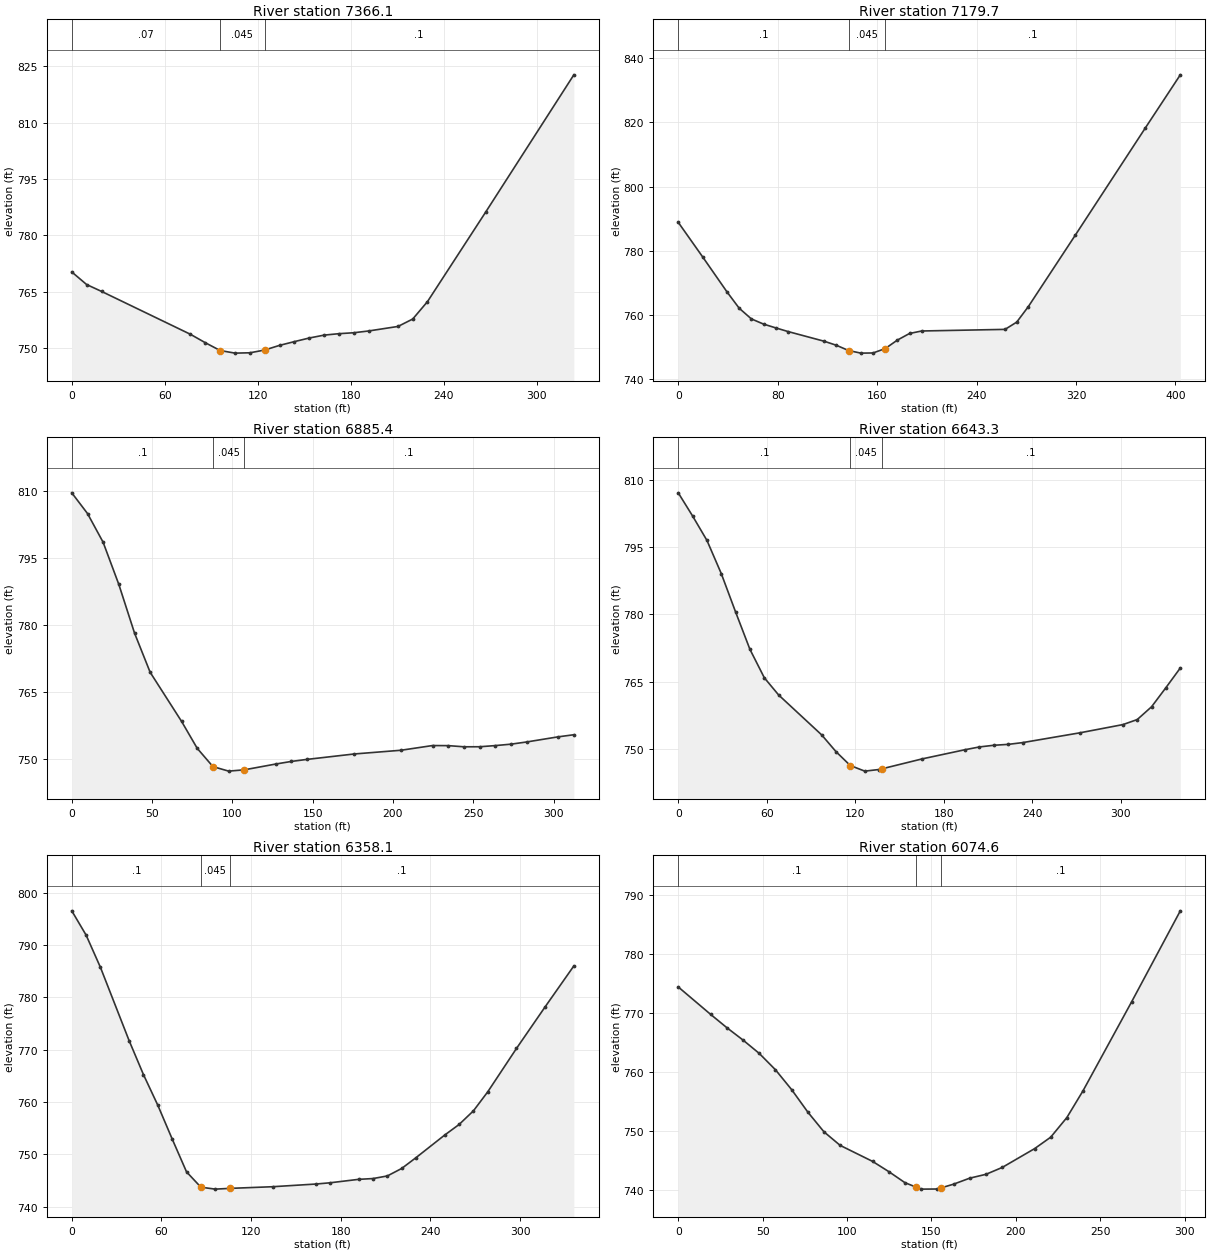
Type RM Length L Ch R = 1 ,7366.1  ,191.9,186.4,180.9
XS GIS Cut Line= 3
     1764962.134       450632.02     1765148.245      450708.409
     1765271.161      450711.881
#Sta/Elev= 21
       0   770.3     9.6  766.95    19.2  765.13    76.6  753.72    86.2  751.48
    95.8   749.4   105.4  748.71     115   748.8   124.5  749.53   134.1  750.77
   143.7  751.77   153.3  752.73   162.9   753.5   172.4  753.88     182  754.13
   191.6   754.6   210.6  755.81   220.1  757.78   229.6   762.4   267.4  786.36
   324.1  822.73
#Mann= 3 , 0 , 0
       0     .07       0    95.8    .045       0   124.5      .1       0
Bank Sta=95.8,124.5
XS Rating Curve= 0 ,0
Exp/Cntr=0.3,0.1

Type RM Length L Ch R = 1 ,7179.7  ,286.4,294.3,302
XS GIS Cut Line= 3
     1764894.842      450834.867     1765117.759      450867.506
     1765296.231      450861.256
#Sta/Elev= 23
       0   788.9    19.6  778.16    39.2  767.26      49  762.18    58.8  758.85
    68.6  757.23    78.4  756.05    88.2  754.92   117.5  751.88   127.3  750.62
   137.1  748.99   146.9  748.19   156.7  748.24   166.5   749.6   176.3  752.25
   186.1  754.31   195.9  755.08   262.9  755.58   272.3  757.84   281.7   762.7
   319.3  784.83   375.7  818.23   403.9   834.8
#Mann= 3 , 0 , 0
       0      .1       0   137.1    .045       0   166.5      .1       0
Bank Sta=137.1,166.5
XS Rating Curve= 0 ,0
Exp/Cntr=0.3,0.1

Type RM Length L Ch R = 1 ,6885.4  ,242.3,242.1,241.7
XS GIS Cut Line= 2
     1764818.349      451067.089      1765093.87      451214.659
#Sta/Elev= 25
       0  809.58     9.8  804.94    19.5  798.52    29.3  789.06    39.1  778.14
    48.8  769.38    68.4  758.36    78.1  752.35    87.9  748.25    97.7  747.24
   107.4  747.53     127  748.83   136.7  749.41   146.5  749.87   175.8  751.08
   205.1  751.92   224.6  752.97   234.4  752.95   244.2  752.69     254   752.7
   263.7  752.96   273.5  753.28   283.2  753.77   302.8  754.92   312.6  755.39
#Mann= 3 , 0 , 0
       0      .1       0    87.9    .045       0   107.4      .1       0
Bank Sta=87.9,107.4
XS Rating Curve= 0 ,0
Exp/Cntr=0.3,0.1

Type RM Length L Ch R = 1 ,6643.3  ,277.4,285.1,292.6
XS GIS Cut Line= 2
     1764705.367      451280.048     1765007.585      451436.881
#Sta/Elev= 26
       0  807.04     9.7  801.91    19.5  796.44    29.2  789.07    38.9  780.54
    48.6  772.25    58.4   765.9    68.1  762.08    97.3   753.2     107  749.48
   116.7  746.39   126.5  745.15   136.2  745.51   138.1  745.66   165.4  747.87
   194.6  749.92   204.3  750.53     214   750.9   223.8   751.1   233.5  751.49
   272.4  753.67   301.6   755.5   311.3  756.62     321  759.46   330.8  763.74
   340.5  768.09
#Mann= 3 , 0 , 0
       0      .1       0   116.7    .045       0   138.1      .1       0
Bank Sta=116.7,138.1
XS Rating Curve= 0 ,0
Exp/Cntr=0.3,0.1

Type RM Length L Ch R = 1 ,6358.1  ,292,283.6,274.5
XS GIS Cut Line= 2
     1764572.698      451485.391     1764803.253      451729.836
#Sta/Elev= 26
       0  796.51     9.6  791.87    19.2   785.7    38.4  771.69      48   765.2
    57.6  759.35    67.2  752.91    76.8  746.63    86.4   743.7      96  743.33
   105.6  743.47   134.4  743.79   163.2   744.3   172.8  744.54     192   745.2
   201.6  745.35   211.2  745.85   220.8  747.28   230.4  749.35   249.6  753.67
   259.2  755.68   268.8  758.29   278.4  761.93   297.6  770.21   316.8  778.17
     336  785.98
#Mann= 3 , 0 , 0
       0      .1       0    86.4    .045       0   105.6      .1       0
Bank Sta=86.4,105.6
XS Rating Curve= 0 ,0
Exp/Cntr=0.3,0.1

Type RM Length L Ch R = 1 ,6074.6  ,56.5,56.5,56.5
XS GIS Cut Line= 2
     1764432.439      451760.812      1764702.89      451884.508
#Sta/Elev= 27
       0  774.44    19.2  769.79    28.8  767.54    38.4  765.44      48  763.18
    57.6  760.41    67.2  757.04    76.8  753.23    86.3  749.91    95.9  747.61
   115.1   744.9   124.7  743.17   134.3  741.29   140.8  740.55   143.9   740.2
   153.5  740.22   155.8  740.42   163.1  741.04   172.7  742.06   182.3  742.71
   191.9  743.87   211.1  747.06   220.6  748.99   230.2  752.32   239.8  756.87
   268.6  771.94   297.4  787.33
#Mann= 3 , 0 , 0
       0      .1       0   140.8    .045       0   155.8      .1       0
Bank Sta=140.8,155.8
XS Rating Curve= 0 ,0
Exp/Cntr=0.3,0.1