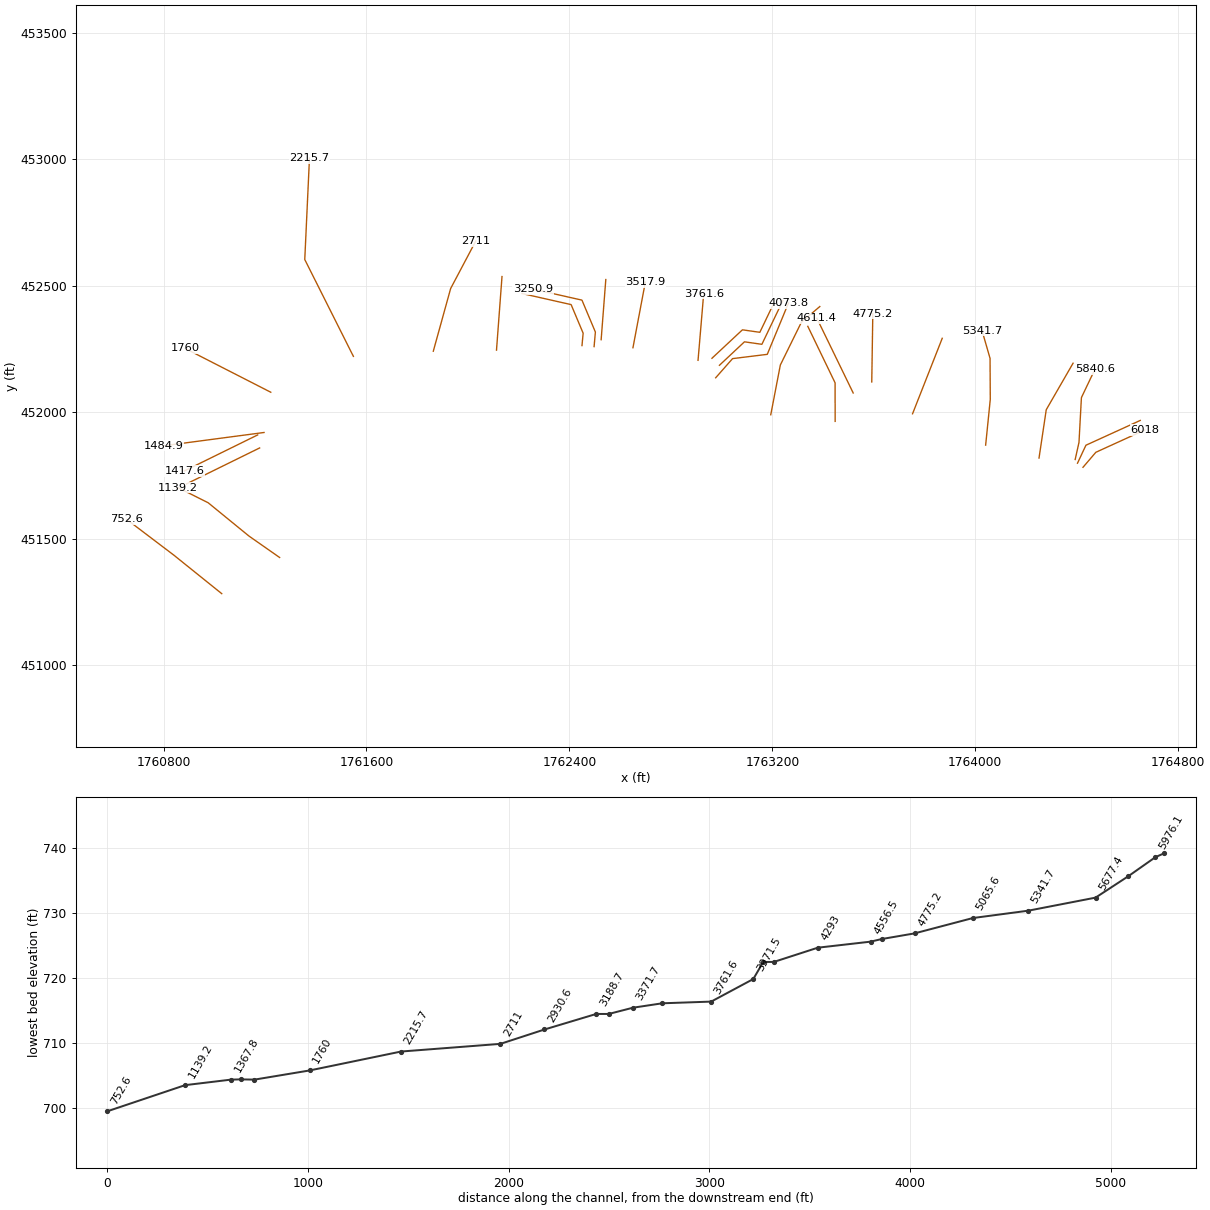
HEC-RAS study BRIERCK.prj: BRIERCK

--- BRIERCK.g01 (geometry) --- (continued)

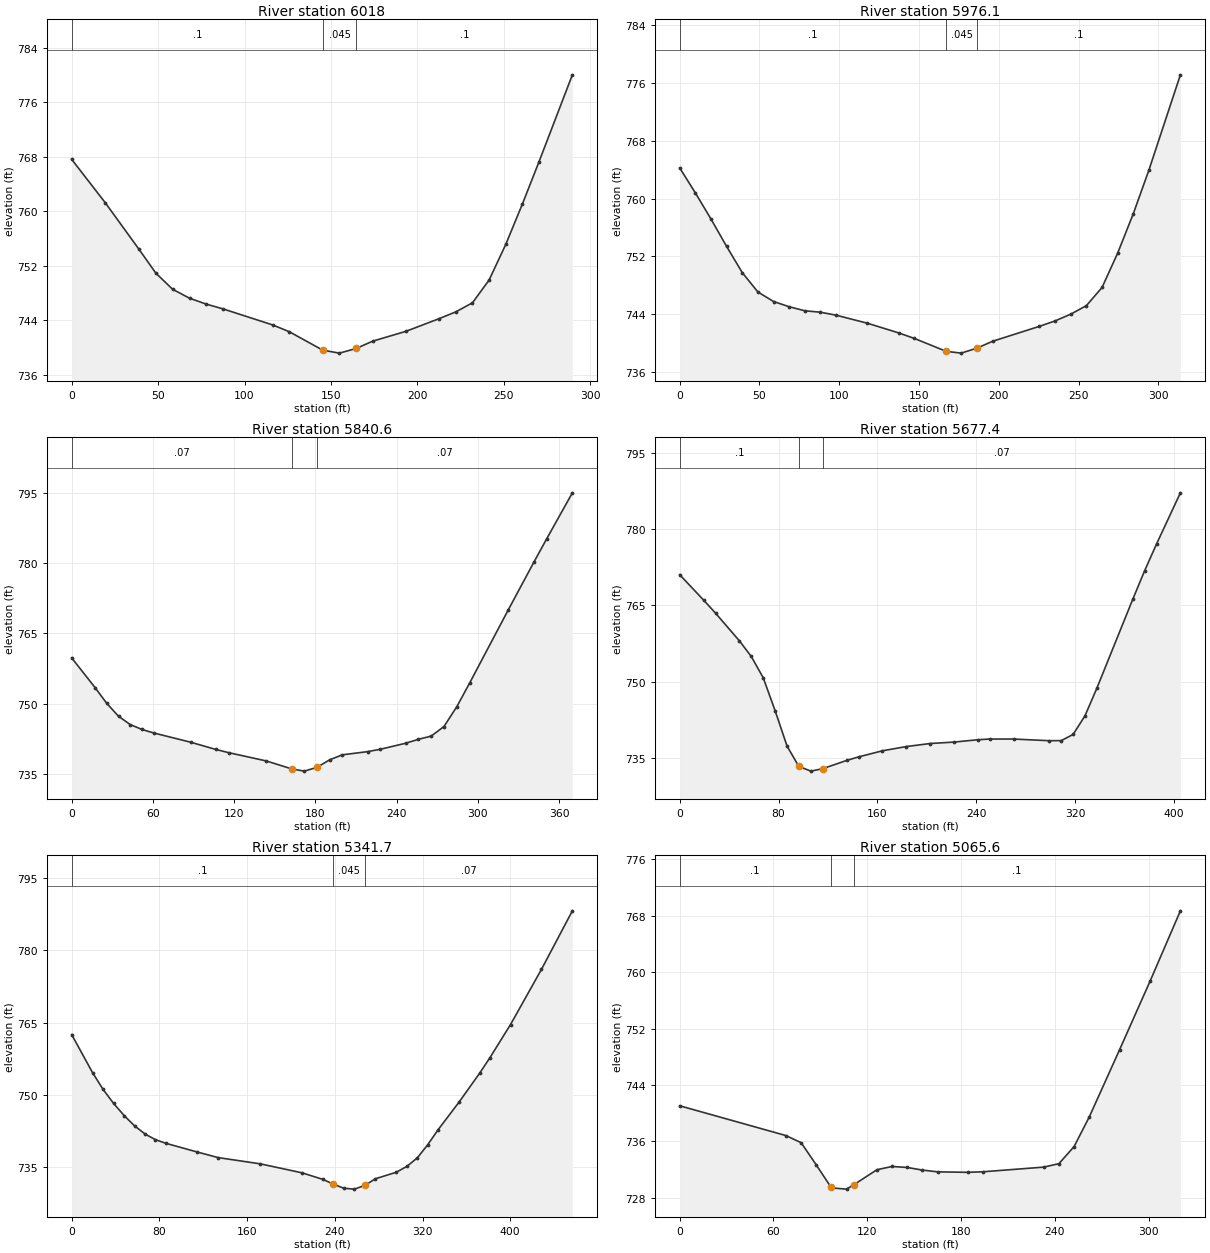
Type RM Length L Ch R = 1 ,6018    ,42.1,41.9,42.1
XS GIS Cut Line= 3
     1764424.757      451783.276     1764475.348      451842.556
      1764667.89      451930.619
#Sta/Elev= 23
       0  767.63    19.5  761.24      39  754.41    48.7  750.93    58.4  748.56
    68.2  747.25    77.9  746.38    87.6  745.68   116.4  743.32     126  742.32
   145.3  739.62   154.9  739.19   164.6  739.87   174.2  740.95   193.4  742.39
   212.7  744.26   222.3  745.25   231.9  746.58   241.5  749.91   251.2  755.17
   260.8  761.09   270.4  767.28   289.7  780.04
#Mann= 3 , 0 , 0
       0      .1       0   145.3    .045       0   164.6      .1       0
Bank Sta=145.3,164.6
XS Rating Curve= 0 ,0
Exp/Cntr=0.3,0.1

Type RM Length L Ch R = 1 ,5976.1  ,110.4,135.5,159.8
XS GIS Cut Line= 3
      1764403.09      451799.526     1764436.357      451870.505
      1764650.39      451968.396
#Sta/Elev= 27
       0  764.24     9.8  760.79    19.6  757.17    29.4  753.38    39.2  749.76
      49  747.08    58.8  745.76    68.6  745.04    78.4  744.48    88.2  744.28
      98  743.87   117.6  742.76   137.2  741.42     147  740.66     167  738.87
   176.4  738.62   186.3  739.31   196.1  740.26   225.5  742.33   235.3  743.08
   245.1  744.01   254.9  745.19   264.7   747.7   274.5  752.46   284.3  757.91
   294.1  763.96   313.8  777.12
#Mann= 3 , 0 , 0
       0      .1       0     167    .045       0   186.3      .1       0
Bank Sta=167,186.3
XS Rating Curve= 0 ,0
Exp/Cntr=0.3,0.1

Type RM Length L Ch R = 1 ,5840.6  ,165,163.1,160.8
XS GIS Cut Line= 4
     1764393.924      451814.109     1764408.924      451881.609
     1764418.507      452058.692     1764471.424      452169.942
#Sta/Elev= 28
       0  759.79    17.3  753.45    25.9   750.1    34.6  747.36    43.2   745.6
    51.9  744.55    60.5  743.81    87.8  741.84   106.5  740.29   115.8  739.62
   143.8  737.84   162.5  736.15   171.8  735.68   181.2   736.5   190.5  738.09
   199.8  739.15   218.5  739.83   227.8  740.33   246.5  741.61     256  742.45
   265.4  743.13   274.9  745.18   284.4  749.41   293.9  754.47   322.3  769.98
   341.2  780.13   350.7  785.13   369.7  794.94
#Mann= 3 , 0 , 0
       0     .07       0   162.5    .045       0   181.2     .07       0
Bank Sta=162.5,181.2
XS Rating Curve= 0 ,0
Exp/Cntr=0.3,0.1

Type RM Length L Ch R = 1 ,5677.4  ,331.8,335.7,339
XS GIS Cut Line= 3
     1764251.382      451819.823     1764279.854      452010.795
     1764385.583      452194.649
#Sta/Elev= 29
       0  771.01    19.3  766.03      29  763.45    48.3  758.01    57.9  754.94
    67.6  750.74    77.2  744.28    86.9   737.3    96.4  733.31   106.2  732.39
   115.8  732.88   135.2   734.5   144.8  735.19   164.1  736.39   183.4  737.22
   202.7  737.82     222   738.1   241.3  738.56   250.9   738.7   270.2   738.7
   299.1  738.37   308.8  738.39   318.4  739.61     328  743.27   337.7  748.75
   366.6  766.14   376.2  771.75   385.9  777.05   405.2  787.11
#Mann= 3 , 0 , 0
       0      .1       0    96.4    .045       0   115.8     .07       0
Bank Sta=96.4,115.8
XS Rating Curve= 0 ,0
Exp/Cntr=0.3,0.1

Type RM Length L Ch R = 1 ,5341.7  ,284.5,276.1,267.3
XS GIS Cut Line= 4
     1764040.965      451870.865     1764059.195       452051.42
     1764058.326      452213.747     1764027.076      452322.254
#Sta/Elev= 30
       0   762.5    19.1  754.56    28.6  751.12    38.2   748.2    47.8  745.68
    57.3  743.54    66.9  741.84    76.4  740.66      86   739.9   114.6  738.09
   133.7  736.93   171.9  735.64   210.1  733.77   229.2   732.4   238.8   731.4
   248.3  730.56   257.9  730.38   267.4  731.16     277  732.53   296.1  733.89
   305.6  735.09   315.2  736.86   324.7  739.59   334.2  742.72   353.2  748.43
     372  754.44   381.4  757.67   400.3   764.6   428.5  776.06   456.7  788.23
#Mann= 3 , 0 , 0
       0      .1       0   238.8    .045       0   267.4     .07       0
Bank Sta=238.8,267.4
XS Rating Curve= 0 ,0
Exp/Cntr=0.3,0.1

Type RM Length L Ch R = 1 ,5065.6  ,282.4,290.5,298.5
XS GIS Cut Line= 2
     1763752.806      451994.823      1763869.82      452293.052
#Sta/Elev= 22
       0  741.06      68  736.84    77.7  735.83    87.4  732.68    96.6  729.59
    97.1  729.42   106.8  729.25   111.6   729.9   126.2     732   135.9  732.46
   145.6  732.32   155.3  731.95     165   731.7   184.4  731.63   194.2  731.71
     233  732.37   242.7  732.86   252.4  735.29   262.1  739.48   281.5  749.01
     301  758.72   320.4  768.69
#Mann= 3 , 0 , 0
       0      .1       0    96.6    .045       0   111.6      .1       0
Bank Sta=96.6,111.6
XS Rating Curve= 0 ,0
Exp/Cntr=0.3,0.1

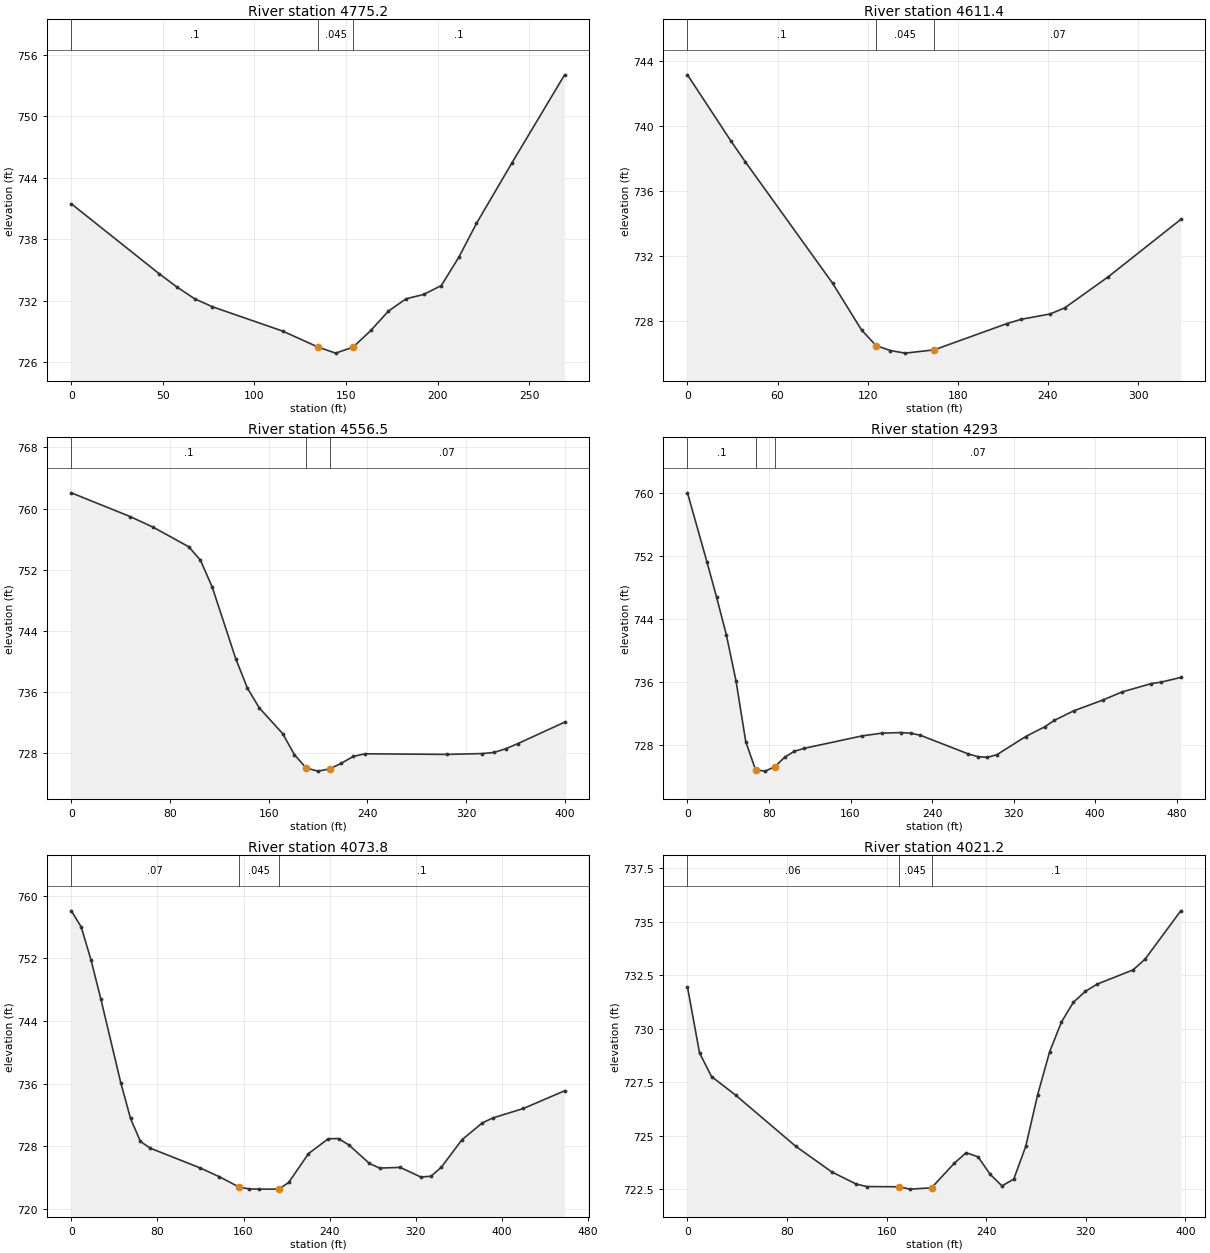
Type RM Length L Ch R = 1 ,4775.2  ,156.7,163.7,168.9
XS GIS Cut Line= 2
     1763591.983      452120.611     1763596.101      452389.911
#Sta/Elev= 18
       0  741.47    48.1  734.62    57.7  733.34    67.3   732.2      77  731.42
   115.4  729.04   134.7  727.48   144.3  726.89   153.9  727.48   163.5   729.1
   173.1  730.99   182.8   732.2   192.4  732.62     202  733.49   211.6  736.27
   221.2  739.56   240.5  745.45   269.3  754.06
#Mann= 3 , 0 , 0
       0      .1       0   134.7    .045       0   153.9      .1       0
Bank Sta=134.7,153.9
XS Rating Curve= 0 ,0
Exp/Cntr=0.3,0.1

Type RM Length L Ch R = 1 ,4611.4  ,50.8,55,59.9
XS GIS Cut Line= 2
     1763518.772      452076.941     1763375.514      452372.462
#Sta/Elev= 15
       0  743.13      29  739.05    38.6  737.77    96.6  730.32   115.9  727.44
   125.6  726.48   135.1  726.18   144.9  726.02   164.2  726.22   212.5  727.83
   222.2   728.1   241.5  728.43   251.1   728.8   280.1  730.71   328.4  734.24
#Mann= 3 , 0 , 0
       0      .1       0   125.6    .045       0   164.2     .07       0
Bank Sta=125.6,164.2
XS Rating Curve= 0 ,0
Exp/Cntr=0.3,0.1

Type RM Length L Ch R = 1 ,4556.5  ,278.2,263.5,248.3
XS GIS Cut Line= 3
     1763447.679      451964.726     1763447.434       452117.08
     1763339.958       452340.24
#Sta/Elev= 23
       0  762.06    47.6  758.96    66.6  757.54    95.2     755   104.7  753.24
   114.3   749.7   133.3  740.35   142.8  736.49   152.4   733.9   171.4  730.53
   180.9  727.77   190.5  726.02     200  725.62   209.5  725.91     219  726.66
   228.6  727.54   238.1  727.89   304.8  727.81   333.4  727.92   342.9  728.07
   352.4  728.56   361.9  729.21     400  732.03
#Mann= 3 , 0 , 0
       0      .1       0   190.5    .045       0   209.5     .07       0
Bank Sta=190.5,209.5
XS Rating Curve= 0 ,0
Exp/Cntr=0.3,0.1

Type RM Length L Ch R = 1 ,4293    ,247.6,219.2,190.8
XS GIS Cut Line= 4
      1763193.79      451990.838     1763231.568      452187.504
     1763314.436      452356.349     1763387.124      452418.615
#Sta/Elev= 30
       0  760.03    19.1  751.26    28.6  746.76    38.2  741.97    47.7   736.1
    57.2  728.42    66.8  724.86    76.3  724.69    85.8  725.26    95.4  726.46
   104.9  727.21   114.4  727.58   171.6  729.17   190.7  729.51   209.7  729.59
   219.1   729.5   228.5  729.25   275.5  726.88   284.9  726.53   294.3  726.44
   303.7  726.78   331.9  729.08   350.7  730.33   360.1  731.14   378.9  732.34
   407.5  733.71   426.6  734.75   455.3  735.81   464.9  735.99   484.1  736.59
#Mann= 3 , 0 , 0
       0      .1       0    66.8    .045       0    85.8     .07       0
Bank Sta=66.8,85.8
XS Rating Curve= 0 ,0
Exp/Cntr=0.3,0.1

Type RM Length L Ch R = 1 ,4073.8  ,58.7,52.6,46.4
XS GIS Cut Line= 4
     1762976.673      452137.043     1763043.321       452212.78
      1763180.08      452229.658     1763263.695      452432.608
#Sta/Elev= 30
       0  758.07     9.2     756    18.3  751.78    27.5  746.76    45.9  736.11
      55  731.53    64.2  728.59    73.4  727.73   119.3  725.23   137.6  724.08
     156  722.75   165.2  722.53   174.4   722.5   192.8   722.5   201.9  723.35
   220.3  727.04   238.7  728.94   248.2  728.96   257.8  728.15   276.9  725.78
   286.4  725.19   305.5  725.28   324.6  724.05   334.1  724.15   343.7   725.3
   362.8   728.8   381.8  730.97   391.4  731.59     420  732.81   458.2  735.07
#Mann= 3 , 0 , 0
       0     .07       0     156    .045       0   192.8      .1       0
Bank Sta=156,192.8
XS Rating Curve= 0 ,0
Exp/Cntr=0.3,0.1

Type RM Length L Ch R = 1 ,4021.2  ,55.1,49.7,49.1
XS GIS Cut Line= 4
      1762991.53      452186.473     1763090.195      452279.149
     1763158.816      452269.317     1763241.472      452442.053
#Sta/Elev= 27
       0  731.94     9.7  728.86    19.3  727.76    38.7  726.89      87   724.5
     116   723.3   135.4  722.74     144  722.62     170  722.61   178.7   722.5
     196  722.56   214.3  723.71   223.8   724.2   233.4  724.01     243   723.2
   252.6  722.65   262.1  722.97   271.7   724.5   281.3  726.92   290.9  728.92
   300.4  730.31     310  731.23   319.6  731.74   329.2  732.08   357.9  732.74
   367.5  733.24   396.2   735.5
#Mann= 3 , 0 , 0
       0     .06       0     170    .045       0     196      .1       0
Bank Sta=170,196
XS Rating Curve= 0 ,0
Exp/Cntr=0.3,0.1

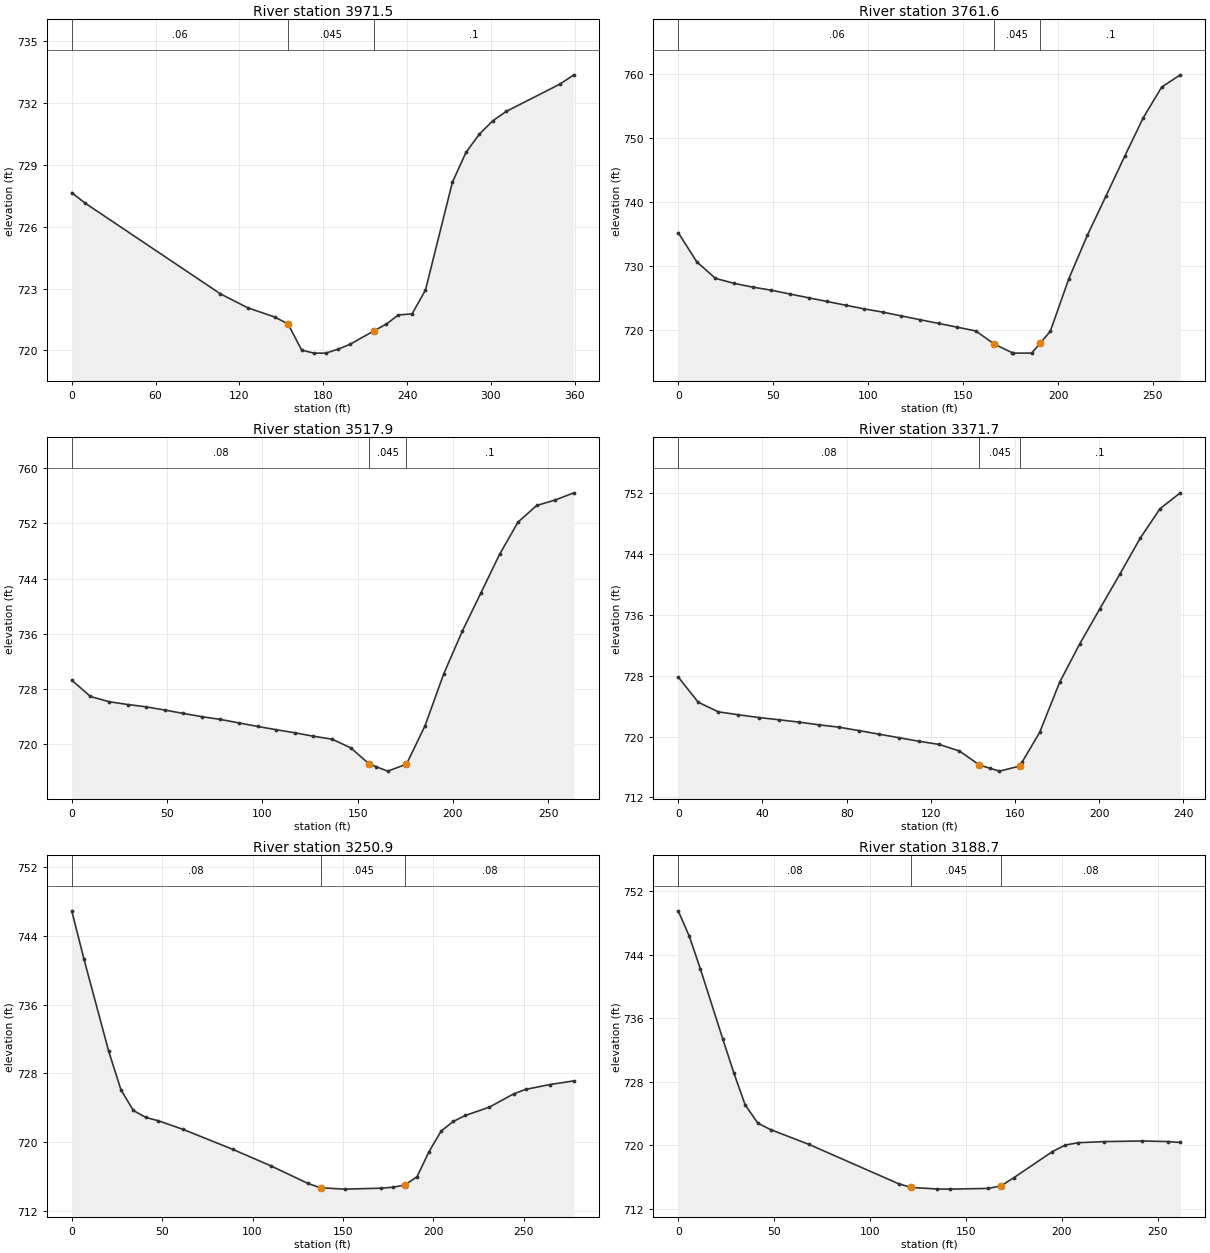
Type RM Length L Ch R = 1 ,3971.5  ,167.3,209.9,247.3
XS GIS Cut Line= 4
     1762962.007      452214.181     1763082.107      452326.597
     1763150.728      452316.765     1763204.939      452429.924
#Sta/Elev= 23
       0  727.64     9.7  727.13   106.4  722.74   125.8  722.07   145.2  721.62
   154.8  721.28   164.5  720.02   173.2  719.87   181.8  719.87   190.5  720.06
   199.2   720.3   216.5  720.96   225.2  721.28   233.8  721.72   243.5  721.77
   253.1  722.92   272.4  728.15   282.1  729.59   291.7  730.48   301.4  731.13
     311  731.58   349.6  732.91   359.3  733.35
#Mann= 3 , 0 , 0
       0     .06       0   154.8    .045       0   216.5      .1       0
Bank Sta=154.8,216.5
XS Rating Curve= 0 ,0
Exp/Cntr=0.3,0.1

Type RM Length L Ch R = 1 ,3761.6  ,245.8,243.7,241.3
XS GIS Cut Line= 2
     1762907.146      452205.992     1762929.438      452469.499
#Sta/Elev= 30
       0   735.2     9.8  730.64    19.6  728.07    29.4  727.29    39.2  726.71
      49  726.22    58.8  725.63    68.6  725.04    78.4  724.46    88.2  723.88
    97.9  723.31   107.7   722.8   117.5  722.21   127.3  721.62   137.1  721.04
   146.9  720.45   156.7  719.86   166.5   717.8   175.7  716.49   176.3   716.4
   186.1   716.4   190.7  717.99   195.9  719.79   205.7  728.02   215.5  734.83
   225.3  740.95   235.1  747.13   244.9  753.15   254.6  757.93   264.4  759.84
#Mann= 3 , 0 , 0
       0     .06       0   166.5    .045       0   190.7      .1       0
Bank Sta=166.5,190.7
XS Rating Curve= 0 ,0
Exp/Cntr=0.3,0.1

Type RM Length L Ch R = 1 ,3517.9  ,143.6,146.2,148.6
XS GIS Cut Line= 2
     1762650.552      452255.833     1762699.276      452514.659
#Sta/Elev= 30
       0   729.3     9.8  726.94    19.5  726.19    29.3  725.78      39  725.44
    48.8  724.98    58.5  724.49    68.3  724.02      78  723.62    87.8  723.11
    97.6   722.6   107.3  722.13     117  721.69   126.8  721.19   136.6  720.76
   146.3  719.52   156.1  717.16   159.7  716.78   165.8  716.14   174.7  717.06
   175.6  717.15   185.3  722.69   195.1  730.19   204.8  736.35   214.6   741.9
   224.4  747.49   234.1  752.17   243.9  754.58   253.6  755.37   263.4  756.41
#Mann= 3 , 0 , 0
       0     .08       0   156.1    .045       0   175.6      .1       0
Bank Sta=156.1,175.6
XS Rating Curve= 0 ,0
Exp/Cntr=0.3,0.1

Type RM Length L Ch R = 1 ,3371.7  ,79.6,120.8,176.2
XS GIS Cut Line= 2
      1762525.15       452287.51     1762543.483      452525.288
#Sta/Elev= 28
       0  727.83     9.5  724.52    19.1  723.25    28.6  722.87    38.2  722.51
    47.7  722.22    57.2  721.91    66.8  721.55    76.3  721.24    85.8  720.79
    95.4  720.32   104.9  719.85   114.5  719.38     124  718.97   133.6   718.1
   143.1  716.26   148.3  715.82   152.6  715.46   162.2  716.12   163.3  716.63
   171.7  720.56   181.2  727.16   190.8  732.23   200.3  736.82   209.9  741.42
   219.4  746.07   228.9  749.98   238.5  752.05
#Mann= 3 , 0 , 0
       0     .08       0   143.1    .045       0   162.2      .1       0
Bank Sta=143.1,162.2
XS Rating Curve= 0 ,0
Exp/Cntr=0.3,0.1

Type RM Length L Ch R = 1 ,3250.9  ,53.5,62.2,45.7
XS GIS Cut Line= 4
     1762497.372      452260.288     1762502.408      452317.847
     1762449.456      452443.948     1762256.053      452487.698
#Sta/Elev= 26
       0  746.92   6.788  741.26  20.436  730.56  27.223  726.06  34.082  723.66
  40.871  722.86    47.8  722.47  61.589  721.46  89.237  719.12 109.955  717.23
 130.673  715.16 137.602  714.66 150.897   714.5 170.978  714.61 177.625  714.72
 184.272  714.98  190.99  715.94 197.636  718.87 204.354  721.27 211.001  722.38
 217.718  723.08 231.012  724.05 244.376  725.59 251.094  726.12 264.458  726.68
 277.752  727.11
#Mann= 3 , 0 , 0
       0     .08       0 137.602    .045       0 184.272     .08       0
Bank Sta=137.602,184.272
XS Rating Curve= 0 ,0
Skew Angle= 45
Exp/Cntr=0.3,0.1

Type RM Length L Ch R = 1 ,3188.7  ,307.8,258,218.9
XS GIS Cut Line= 4
     1762449.595      452264.177     1762454.205      452313.224
     1762406.747       452426.24     1762213.345       452469.99
#Sta/Elev= 23
       0  749.53   5.798  746.31  11.597  742.18  23.193  733.42  28.991  729.12
   34.86  725.12  41.507   722.8  48.154  721.99  68.165  720.13 114.834  715.18
 121.481  714.71 134.845  714.52 141.563   714.5 161.574  714.59 168.221  714.91
 174.938  715.94 194.949  719.21 201.667  720.04 208.314  720.34 221.678  720.48
 241.689  720.56 255.053  720.49   261.7  720.37
#Mann= 3 , 0 , 0
       0     .08       0 121.481    .045       0 168.221     .08       0
Bank Sta=121.481,168.221
XS Rating Curve= 0 ,0
Skew Angle= 45
Exp/Cntr=0.3,0.1

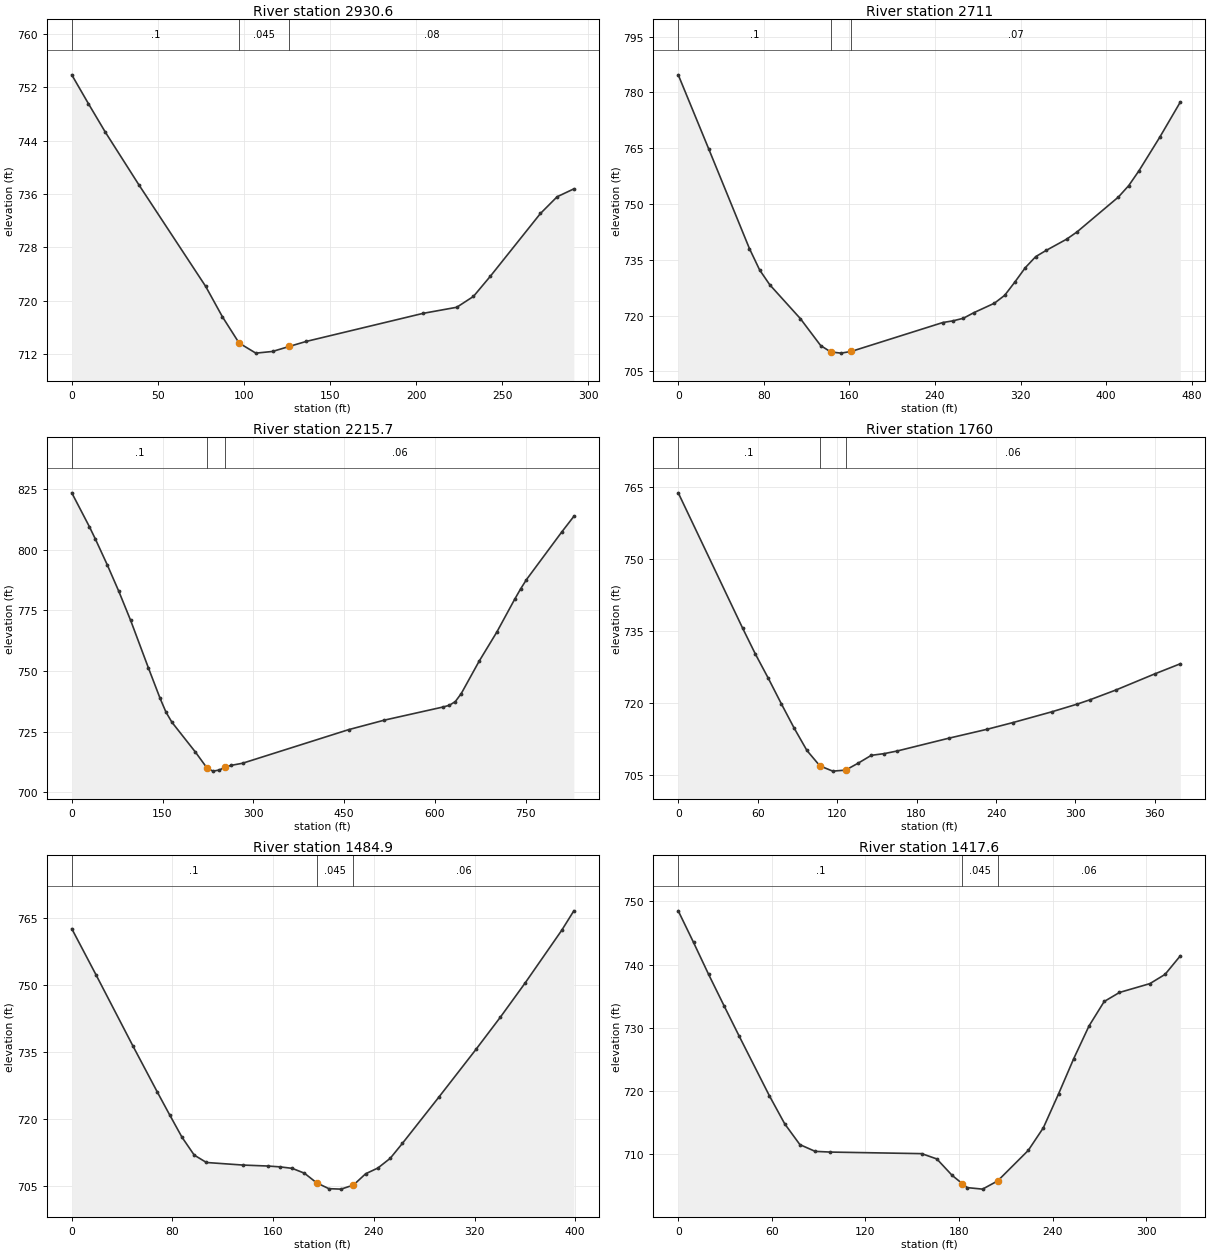
Type RM Length L Ch R = 1 ,2930.6  ,224.3,219.7,215.4
XS GIS Cut Line= 2
     1762112.597      452246.235     1762134.299      452537.034
#Sta/Elev= 18
       0  753.86     9.7  749.52    19.4   745.3    38.9  737.39    77.8  722.11
    87.5  717.56    97.2  713.62   106.9  712.11   116.6  712.36   126.4  713.12
   136.1  713.86   204.1  718.08   223.6  718.99   233.3  720.62     243  723.61
   272.2  733.06   281.9  735.57   291.6  736.75
#Mann= 3 , 0 , 0
       0      .1       0    97.2    .045       0   126.4     .08       0
Bank Sta=97.2,126.4
XS Rating Curve= 0 ,0
Exp/Cntr=0.3,0.1

Type RM Length L Ch R = 1 ,2711    ,478.1,495.2,511.3
XS GIS Cut Line= 3
      1761863.42      452242.047     1761931.796      452489.689
        1762031.      452677.659
#Sta/Elev= 27
       0  784.72    28.6  764.73    66.6  737.99    76.1  732.26    85.6  728.27
   114.2  719.17   133.2  711.92   142.7  710.21   152.2   709.9   161.8  710.36
   247.4  718.13   256.9  718.58   266.6  719.28   276.2  720.75   295.6  723.32
   305.2  725.44   314.9  729.08   324.5  732.88   334.2  735.84   343.9   737.5
   363.2  740.55   372.8  742.48   411.5  751.86   421.2  754.95   430.8  758.95
   450.1  767.91   469.4   777.4
#Mann= 3 , 0 , 0
       0      .1       0   142.7    .045       0   161.8     .07       0
Bank Sta=142.7,161.8
XS Rating Curve= 0 ,0
Exp/Cntr=0.3,0.1

Type RM Length L Ch R = 1 ,2215.7  ,441.1,455.8,470
XS GIS Cut Line= 3
     1761548.396      452221.756     1761356.729      452604.395
     1761375.298      453005.436
#Sta/Elev= 30
       0  823.48    29.2  809.47    38.9  804.47    58.4  793.92    77.8  782.81
    97.3  770.84   126.4  751.42   145.9  738.73   155.6  733.07   165.4  728.89
   204.2   716.6   223.7  709.91   233.4  708.72   243.2  709.15   252.9  710.23
   262.6  711.06   282.1  711.97   457.3  725.82   516.1  729.73     614   735.2
   623.8  735.88   633.6   737.4   643.4  740.71   672.8  753.99   702.1  766.04
   731.5  779.52   741.3   783.8   751.1  787.68   809.8  807.46   829.4  813.78
#Mann= 3 , 0 , 0
       0      .1       0   223.7    .045       0   252.9     .06       0
Bank Sta=223.7,252.9
XS Rating Curve= 0 ,0
Exp/Cntr=0.3,0.1

Type RM Length L Ch R = 1 ,1760    ,260.8,275.1,288.7
XS GIS Cut Line= 2
     1761222.817      452079.858     1760885.317      452252.774
#Sta/Elev= 23
       0   763.8    48.6  735.62    58.3  730.19    68.1  725.12    77.8  719.88
    87.5   714.8    97.2  710.11     107   706.9   116.7  705.81   126.4  706.02
   136.1   707.5   145.8   709.1   155.6  709.46   165.3     710   204.2  712.66
   233.4  714.54   252.8  715.93     282  718.16   301.4  719.78   311.2   720.7
   330.6  722.72   359.8  726.06   379.2  728.18
#Mann= 3 , 0 , 0
       0      .1       0     107    .045       0   126.4     .06       0
Bank Sta=107,126.4
XS Rating Curve= 0 ,0
Exp/Cntr=0.3,0.1

Type RM Length L Ch R = 1 ,1484.9  ,59.7,67.2,74.5
XS GIS Cut Line= 2
     1761196.311      451920.848     1760800.894      451868.348
#Sta/Elev= 27
       0  762.66    19.5  752.22    48.6  736.42    68.1  726.05    77.8     721
    87.6     716    97.3  712.01     107  710.36   136.2  709.78   155.7  709.57
   165.4  709.38   175.1  709.05   184.8  707.97   194.6   705.8   204.3   704.5
     214   704.4   223.8  705.32   233.5  707.84   243.2  709.12     253  711.29
   262.7  714.64   291.9  725.07   321.1  735.65   340.5  742.86     360  750.44
   389.2  762.28   398.9  766.66
#Mann= 3 , 0 , 0
       0      .1       0   194.6    .045       0   223.8     .06       0
Bank Sta=194.6,223.8
XS Rating Curve= 0 ,0
Exp/Cntr=0.3,0.1

Type RM Length L Ch R = 1 ,1417.6  ,49.8,49.8,49.7
XS GIS Cut Line= 2
      1761171.08      451911.189     1760882.336      451768.911
#Sta/Elev= 27
       0  748.52     9.8  743.52    19.5  738.44    29.3  733.52      39  728.71
    58.5   719.2    68.3  714.77      78  711.49    87.8  710.42    97.5  710.31
   156.1  710.06   165.8  709.22   175.6  706.62   182.1  705.32   185.3  704.68
   195.1  704.44   204.8  705.74   224.4  710.57   234.1  714.16   243.9  719.56
   253.6  725.13   263.4   730.3   273.1  734.16   282.9  735.59   302.4  736.99
   312.1  738.45   321.9  741.39
#Mann= 3 , 0 , 0
       0      .1       0   182.1    .045       0   204.8     .06       0
Bank Sta=182.1,204.8
XS Rating Curve= 0 ,0
Exp/Cntr=0.3,0.1

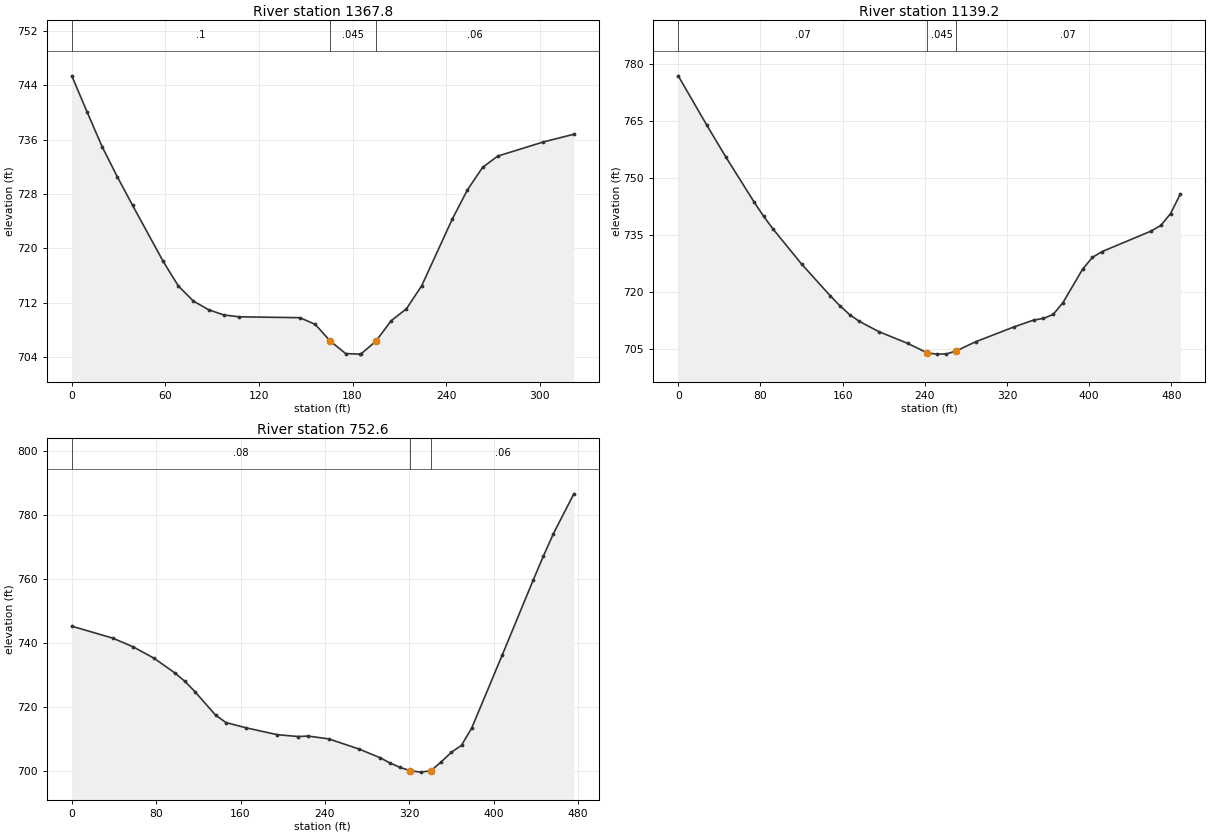
Type RM Length L Ch R = 1 ,1367.8  ,254.5,228.6,202.7
XS GIS Cut Line= 2
     1761178.788      451859.731     1760890.044      451717.453
#Sta/Elev= 27
       0  745.41     9.8   740.1    19.5  734.95    29.3  730.49      39  726.32
    58.5  718.11    68.3  714.45      78  712.21    87.8  710.94    97.5  710.17
   107.3   709.9   146.3  709.77   156.1  708.78   165.8  706.31   175.6  704.48
     185   704.4   185.3   704.4   195.1  706.34   204.8  709.33   214.6  711.09
   224.4   714.5   243.9  724.27   253.6  728.57   263.4  731.92   273.1  733.58
   302.4  735.67   321.9   736.8
#Mann= 3 , 0 , 0
       0      .1       0   165.8    .045       0   195.1     .06       0
Bank Sta=165.8,195.1
XS Rating Curve= 0 ,0
Exp/Cntr=0.3,0.1

Type RM Length L Ch R = 1 ,1139.2  ,383.4,386.6,386.1
XS GIS Cut Line= 4
     1761257.616       451426.78     1761136.539      451511.701
     1760975.861      451643.137     1760856.797      451702.938
#Sta/Elev= 30
       0  776.93    27.7  763.97    46.2  755.59    73.9  743.64    83.2  739.86
    92.4   736.5   120.2  727.26   147.9  718.95   157.3  716.32   166.8  713.98
   176.2   712.2   195.1   709.5   223.4  706.38   242.2   703.9   251.7  703.55
   261.1  703.61   270.6  704.39   289.4   706.8   327.2  710.77     346  712.54
   355.5  712.97     365  714.02   374.5  717.15   393.6  725.94   403.1  729.05
   412.6  730.59   460.2  735.99   469.7  737.47   479.2  740.61   488.7  745.74
#Mann= 3 , 0 , 0
       0     .07       0   242.2    .045       0   270.6     .07       0
Bank Sta=242.2,270.6
XS Rating Curve= 0 ,0
Exp/Cntr=0.3,0.1

Type RM Length L Ch R = 1 ,752.6   ,54.8,64.7,77.5
XS GIS Cut Line= 3
     1761029.429      451283.864     1760839.776      451436.711
     1760654.707      451577.336
#Sta/Elev= 30
       0  745.26      39   741.5    58.5  738.74      78  735.22    97.4   730.7
   107.2     728   116.9   724.7   136.4  717.38   146.2  715.07   165.6  713.39
   194.9  711.27   214.4   710.7   224.1  710.83   243.6  709.96   272.6  706.74
     292  704.09   301.7  702.41   311.4     701   321.1  699.97   330.7  699.54
   340.4  699.96   350.1   702.7   359.8  705.73   369.5  707.95   379.2  713.38
   408.2  736.29   437.3  759.57     447  767.12   456.6  774.24     476  786.72
#Mann= 3 , 0 , 0
       0     .08       0   321.1    .045       0   340.4     .06       0
Bank Sta=321.1,340.4
XS Rating Curve= 0 ,0
Exp/Cntr=0.3,0.1