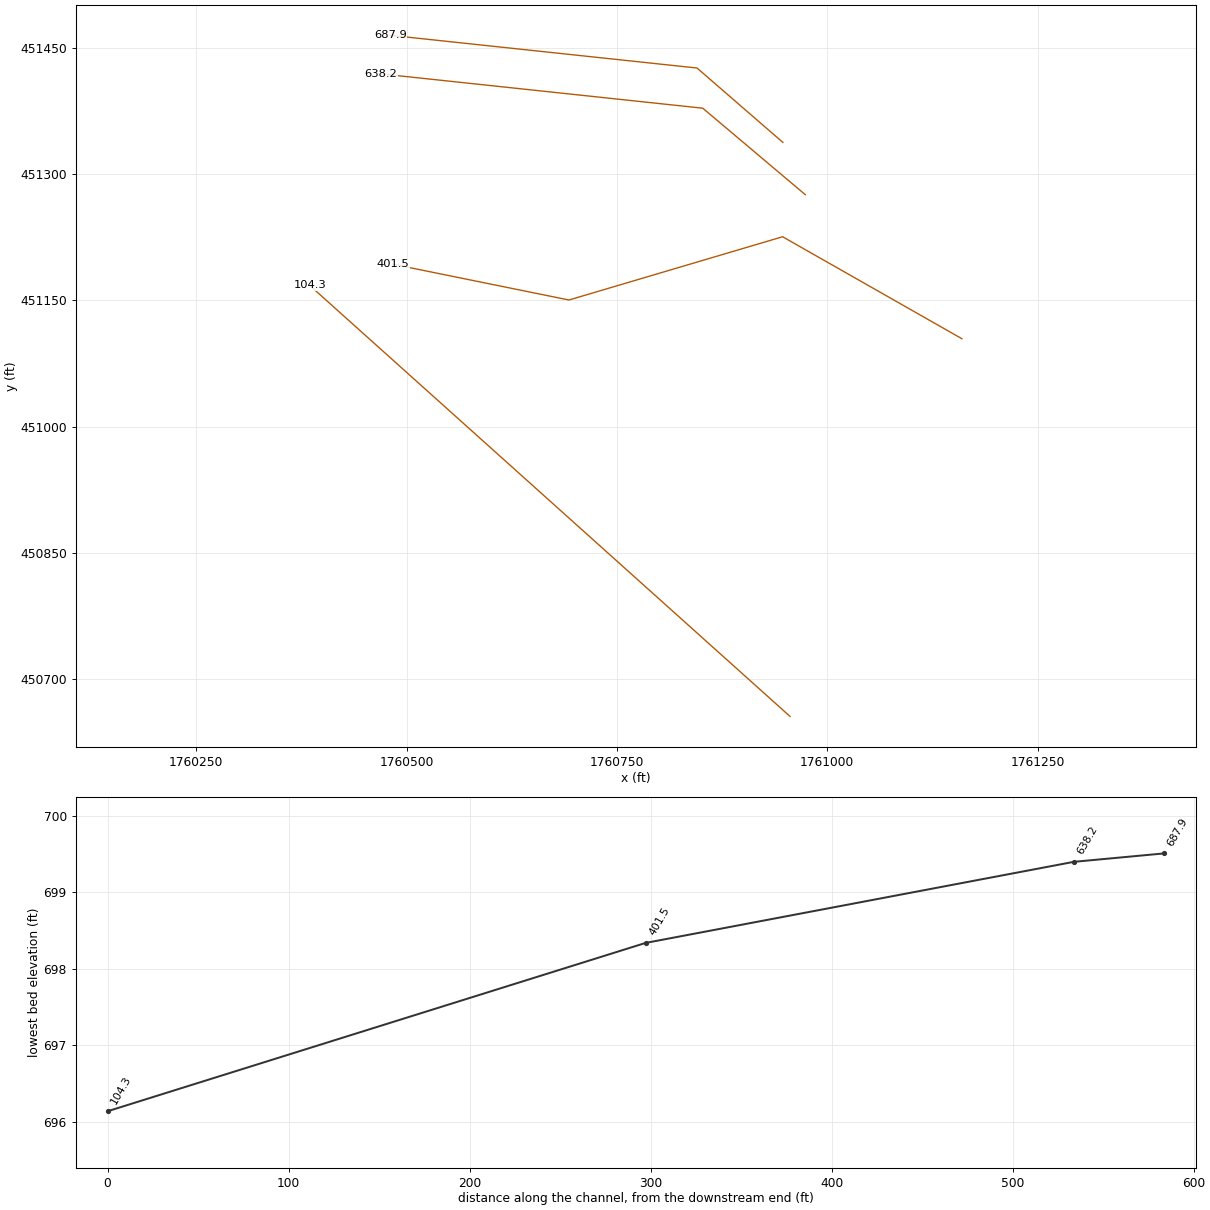
HEC-RAS study BRIERCK.prj: BRIERCK

--- BRIERCK.g01 (geometry) --- (continued)

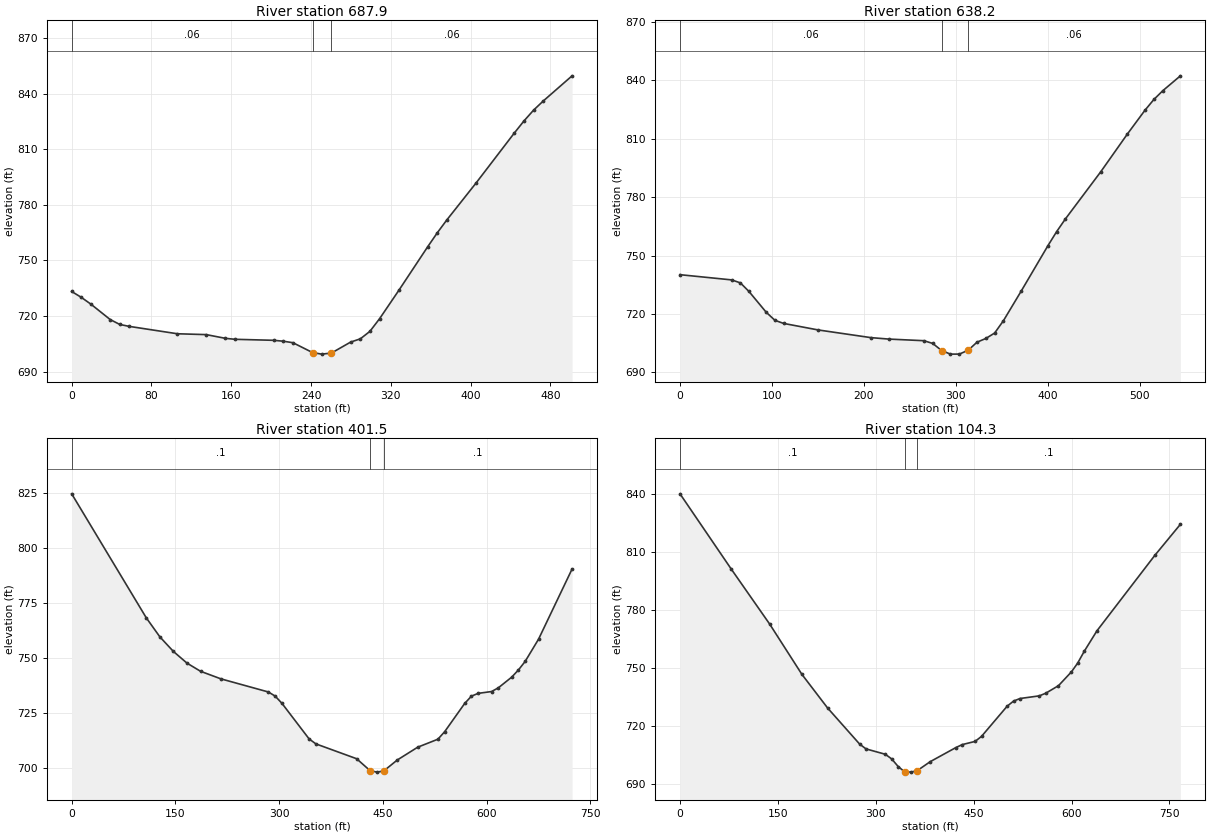
Type RM Length L Ch R = 1 ,687.9   ,50.4,49.8,49.2
XS GIS Cut Line= 3
     1760947.207      451337.753     1760845.245      451426.102
      1760480.52      451465.002
#Sta/Elev= 30
       0  733.28     9.6  730.14    19.3  726.44    38.6  718.16    48.2  715.51
    57.8  714.46     106  710.49   134.9  710.03   154.2  708.02   163.9   707.5
   202.5  706.96   212.1  706.48   221.8  705.67   241.6  700.33   250.7  699.51
   260.4  700.09   279.7  706.01   289.4  707.75     299  711.79   308.7  718.61
     328   733.9   356.9  757.37   366.6  764.96   376.2  771.92   405.2  791.62
   443.8  818.74   453.4   825.2   463.1  831.07   472.8     836   501.7  849.57
#Mann= 3 , 0 , 0
       0     .06       0   241.6    .045       0   260.4     .06       0
Bank Sta=241.6,260.4
XS Rating Curve= 0 ,0
Exp/Cntr=0.3,0.1

Type RM Length L Ch R = 1 ,638.2   ,227.8,236.6,245.3
XS GIS Cut Line= 3
     1760973.934      451275.565     1760852.032      451378.359
     1760469.409      451419.169
#Sta/Elev= 30
       0  740.17    56.3  737.49    65.7  735.95      75  731.56    93.8  720.87
   103.2  716.76   112.6  715.17   150.1  711.82   207.6  707.87   226.8  707.13
   265.3  706.29   274.9  704.88   284.5  701.25   294.1   699.4   303.8  699.42
   313.4  701.39     323  705.53   332.6  707.43   342.2  710.23   351.8   716.6
   371.1  731.77     400  754.95   409.6  762.26   419.2  768.83   457.7  793.06
   486.5  812.33   505.8  824.65   515.4  830.11     525  834.57   544.2  842.23
#Mann= 3 , 0 , 0
       0     .06       0   284.5    .045       0   313.4     .06       0
Bank Sta=284.5,313.4
XS Rating Curve= 0 ,0
Exp/Cntr=0.3,0.1

Type RM Length L Ch R = 1 ,401.5   ,319.9,297.2,273.9
XS GIS Cut Line= 4
      1761160.02      451104.394     1760946.933      451225.582
     1760693.006      451150.401     1760483.805      451192.936
#Sta/Elev= 30
       0  824.52   107.9  768.27   127.5  759.66   147.1  753.04   166.7  747.76
   186.3  744.06   215.7  740.63   284.4  734.67   294.2   732.8     304  729.52
   343.2  713.41     353  711.15   411.9  704.42   431.5  698.98   441.3  698.34
   451.1  698.86   470.7  703.84   500.2  709.64   529.4  713.26   539.1  716.63
   568.2   729.5   577.9  732.79   587.6  734.05     607  734.88   616.7  736.54
   636.1   741.4   645.8  744.65   655.5  748.51   674.9   758.6   723.4  790.44
#Mann= 3 , 0 , 0
       0      .1       0   431.5    .045       0   451.1      .1       0
Bank Sta=431.5,451.1
XS Rating Curve= 0 ,0
Exp/Cntr=0.3,0.1

Type RM Length L Ch R = 1 ,104.3   ,101.3,104.3,107.4
XS GIS Cut Line= 2
     1760955.758       450655.51     1760385.025      451167.653
#Sta/Elev= 30
       0  839.92    78.6  801.01   137.6  772.53   186.8  746.65   226.1  729.31
   275.3  710.61   285.1  708.13   314.6  705.37   324.4  702.96   334.3  699.04
   344.1  696.33   353.9  696.14   363.8  696.96   383.4  701.54   422.7  708.82
   432.6  710.37   452.2  712.01   462.1  714.63   501.4  730.23   511.2  732.85
     521  734.17   550.5  735.54   560.4  736.89     580  740.81   599.7  747.89
   609.5  752.53   619.4  758.54     639  769.19   727.5  808.08   766.8  824.17
#Mann= 3 , 0 , 0
       0      .1       0   344.1    .045       0   363.8      .1       0
Bank Sta=344.1,363.8
XS Rating Curve= 0 ,0
Exp/Cntr=0.3,0.1

Chan Stop Cuts=-1
Use User Specified Reach Order=0
Composite Channel Slope=5